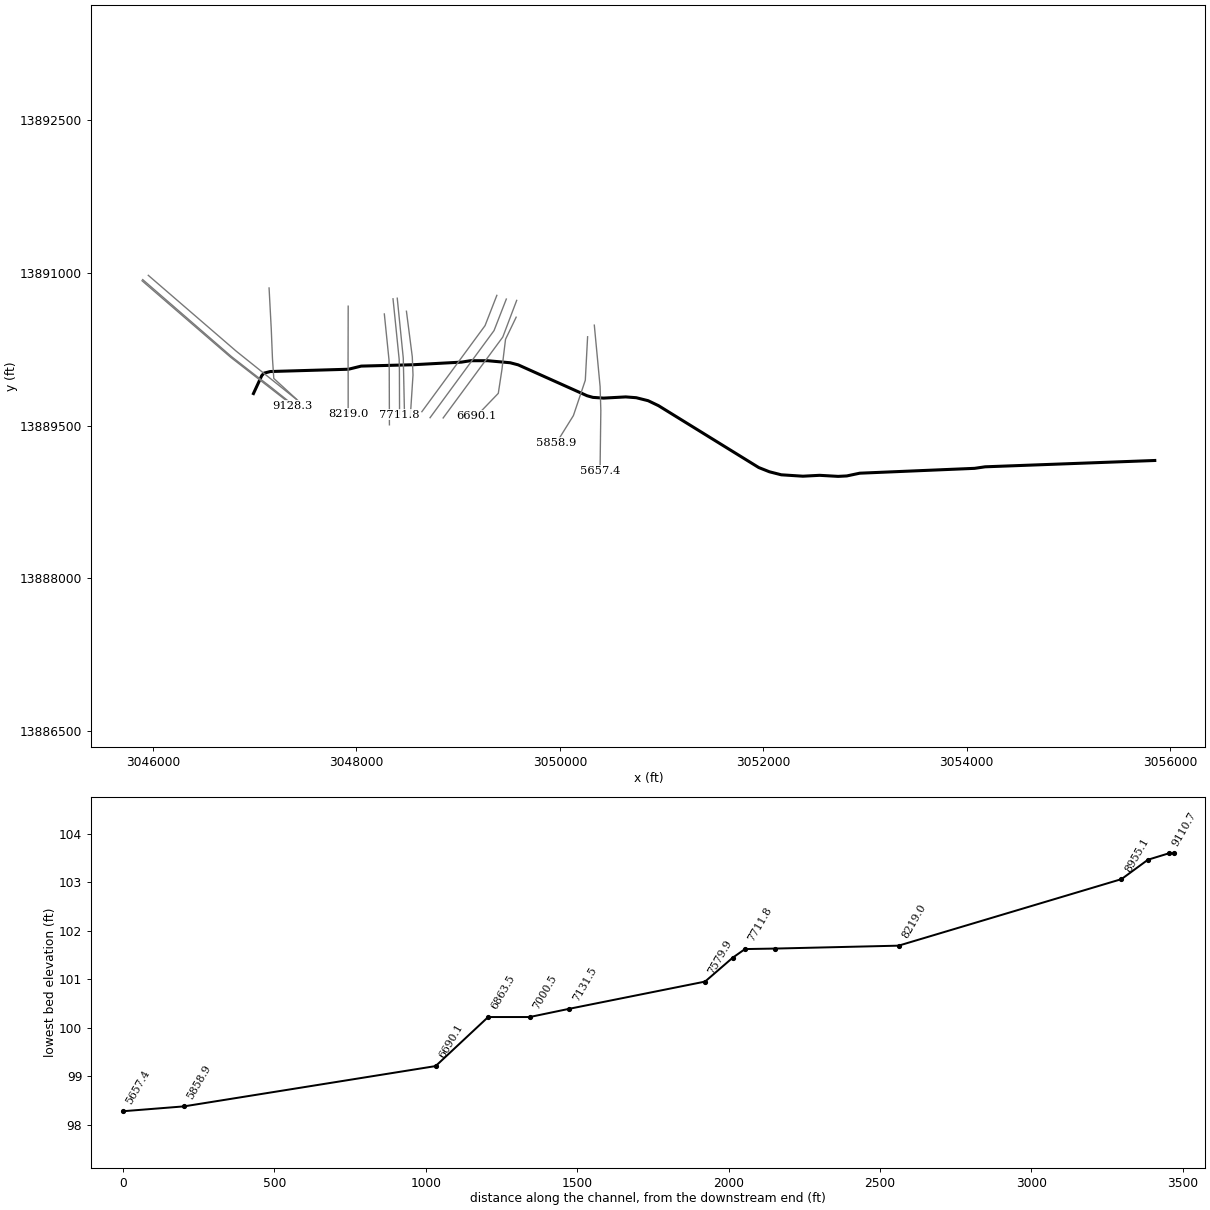
--- E135-00-00.prj (project) ---

Proj Title=E135-00-00
Current Plan=p02
Default Exp/Contr=.3,.1
English Units
Geom File=g01
Flow File=f02
Flow File=f04
Flow File=f01
Plan File=p02
Plan File=p04
Plan File=p01
Y Axis Title=Elevation
X Axis Title(PF)=Main Channel Distance
X Axis Title(XS)=Station
BEGIN DESCRIPTION:
White Oak Bayou Watershed
White Oak Trib. 19.82
HCFCD Unit E135-00-00
Flood Hazard Model
10, 2, 1, 0.2%
Filename E135-00-00
Prepared by:  Mason Liebau  DATE:  March 10, 2004
Reviewed by:  _____________________  DATE:  __________________
STATUS (Final)
END DESCRIPTION:
DSS File=dss
DSS Export Rating Curves= 0
DSS Export Rating Curve Sorted= 0
DSS Export Volume Flow Curves= 0
DXF OffsetX= 0
DXF OffsetY= 0
DXF ScaleX= 1
DXF ScaleY= 10

--- E135-00-00.p02 (plan) ---

Plan Title=Floodway
Version=Version 3.0.1  Mar 2001
Short Identifier=Floodway0607
Geom File=g01
Flow File=f02
Subcritical Flow
K Sum by GR= 0
Std Step Tol= 0.01
Critical Tol= 0.01
Num of Std Step Trials= 20
Max Error Tol= 0.3
Flow Tol Ratio= 0.001
Split Flow NTrial= 30
Split Flow Tol= 0.02
Split Flow Ratio= 0.02
Log Output Level= 0
Friction Slope Method= 1
Unsteady Friction Slope Method= 2
Parabolic Critical Depth
Global Vel Dist= 0 , 0 , 0
Global Log Level= 0
CheckData=True
Encroach Param=-1 ,0,0, 2
Encroach River=E135-00-00
Encroach Reach=Reach - 1
Encroach Node=9128.3
       1  4934.6  5045.4
Encroach Node=9110.7
       1  4934.6  5045.4
Encroach Node=9076.7
       1  4934.6  5045.4
Encroach Node=9042.7
       1  4934.6  5045.4
Encroach Node=8955.1
       1  4959.6  5045.4
Encroach Node=8219.0
       1  4961.4  5035.2
Encroach Node=7810.4
       1  4946.8 5032.94
Encroach Node=7711.8
       1  4947.5  5039.4
Encroach Node=7691.3
       1  4947.5  5039.4
Encroach Node=7670.8
       1  4947.5  5039.4
Encroach Node=7579.9
       1    4953  5040.9
Encroach Node=7131.5
       1 4945.07 5059.33
Encroach Node=7000.5
       1 4956.37  5045.9
Encroach Node=6932.0
       1 4956.37  5045.9
Encroach Node=6863.5
       1 4956.37  5045.9
Encroach Node=6690.1
       1  4953.2    5039
Encroach Node=5858.9
       1  4957.1  5041.5
Encroach Node=5657.4
       1  4958.3 5038.21
Encroach Node=5559
       1  4950.2  5036.6
Encroach Node=5503.0
       1  4950.2  5036.6
Encroach Node=5447
       1  4950.2  5036.6
Encroach Node=5348.6
       1  4946.1  5046.1
Encroach Node=4823.1
       1  4958.2  5038.8
Encroach Node=3974.0
       1  4957.2  5037.7
Encroach Node=3301.1
       1  4951.1  5036.9
Encroach Node=2595.9
       1  4936.9 5036.88
Encroach Node=2496.4
       1  4944.6  5038.6
Encroach Node=2475.4
       1  4944.6  5038.6
Encroach Node=2454.4
       1  4944.6  5038.6
Encroach Node=2354.5
       1  4937.3  5067.3
Encroach Node=2146.0
       1  4951.5  5042.3
Encroach Node=1632.1
       1  4932.6  5079.5
Encroach Node=1525.9
       1  4917.6  5044.8
Encroach Node=1498.9
       1  4917.6  5044.8
Encroach Node=1471.9
       1  4917.6  5044.8
Encroach Node=1375
       1  4924.7  5059.5
Encroach Node=1140.4
       1  4941.9  5050.8
Encroach Node=692.0
       1    4938  5046.5
Encroach Reach=E135-00-00_0007
Encroach Node=9128.3
       1  4934.6  5045.4
Encroach Node=9110.7
       1  4934.6  5045.4
Encroach Node=9076.7
       1  4934.6  5045.4
Encroach Node=9042.7
       1  4934.6  5045.4
Encroach Node=8955.1
       1  4959.6  5045.4
Encroach Node=8219.0
       1  4961.4  5035.2
Encroach Node=7810.4
       1  4946.8 5032.94
Encroach Node=7711.8
       1  4947.5  5039.4
Encroach Node=7691.3
       1  4947.5  5039.4
Encroach Node=7670.8
       1  4947.5  5039.4
Encroach Node=7579.9
       1    4953  5040.9
Encroach Node=7131.5
       1 4945.07 5059.33
Encroach Node=7000.5
       1 4956.37  5045.9
Encroach Node=6932.0
       1 4956.37  5045.9
Encroach Node=6863.5
       1 4956.37  5045.9
Encroach Node=6690.1
       1  4953.2    5039
Encroach Node=5858.9
       1  4957.1  5041.5
Encroach Node=5657.4
       1  4958.3 5038.21
Encroach Node=5559
       1  4950.2  5036.6
Encroach Node=5503.0
       1  4950.2  5036.6
Encroach Node=5447
       1  4950.2  5036.6
Encroach Node=5348.6
       1  4946.1  5046.1
Encroach Node=4823.1
       1  4958.2  5038.8
Encroach Node=3974.0
       1  4957.2  5037.7
Encroach Node=3301.1
       1  4951.1  5036.9
Encroach Node=2595.9
       1  4936.9 5036.88
Encroach Node=2496.4
       1  4944.6  5038.6
Encroach Node=2475.4
       1  4944.6  5038.6
Encroach Node=2454.4
       1  4944.6  5038.6
Encroach Node=2354.5
       1  4937.3  5067.3
Encroach Node=2146.0
       1  4951.5  5042.3
Encroach Node=1632.1
       1  4932.6  5079.5
Encroach Node=1525.9
       1  4917.6  5044.8
Encroach Node=1498.9
       1  4917.6  5044.8
Encroach Node=1471.9
       1  4917.6  5044.8
Encroach Node=1375
       1  4924.7  5059.5
Encroach Node=1140.4
       1  4941.9  5050.8
Encroach Node=692.0
       1    4938  5046.5
Computation Interval=1HOUR
Output Interval=1HOUR
Run HTab= 0
Run UNet= 0
Run PostProcess= 0
UNET Theta= 1
UNET ZTol= 0.02
UNET ZSATol= 0.1
UNET MxIter= 20
UNET MaxInSteps= 20
UNET DtIC= 0
UNET DtMin= 0
UNET MaxCRTS= 20
UNET WFStab= 2
UNET SFStab= 1
UNET WFX= 1
UNET SFX= 1
UNET Convert EG Bridges=-1
UNET Use Existing IB Tables=-1
Instantaneous Interval=1HOUR
Write IC File= 0
IC Time=0
Write Velocity= 0
Write Detailed= 0

--- E135-00-00.p01 (plan) ---

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Plan Title=FEMA Effective June 2007
Geom File=g01
Flow File=f01
Encroach Param=-1 ,0,0, 0
DSS File=dss

--- E135-00-00.p04 (plan) ---

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Plan Title=Storage Routing
Program Version=3.13
Short Identifier=Store_Rout
Geom File=g01
Flow File=f04
Unsteady Bridges Friction Slope Method= 1
Encroach Param=-1 ,0,0, 0
UNET Theta Warmup= 1
UNET DSS MLevel= 4
UNET DZMax Abort= 100
UNET Froude Reduction=False
UNET Froude Limit= 1
UNET Froude Power= 10
Echo Input=False
Echo Output=False
Detailed Automatic Start=False, 10

--- E135-00-00.f02 (steady flow) ---

Flow Title=Floodway
Version=Version 3.0.1  Mar 2001
Number of Profiles= 2
Profile Names=1PCT_100yr, 1PCTFloodway_100yrFW
River Rch & RM=E135-00-00,E135-00-00_0007       ,9128.3
    1220    1220
River Rch & RM=E135-00-00,E135-00-00_0007       ,8955.1
    1290    1290
River Rch & RM=E135-00-00,E135-00-00_0007       ,8219
    1350    1350
River Rch & RM=E135-00-00,E135-00-00_0007       ,7711.8
    1360    1360
River Rch & RM=E135-00-00,E135-00-00_0007       ,7579.9
    1420    1420
River Rch & RM=E135-00-00,E135-00-00_0007       ,7000.5
    1460    1460
River Rch & RM=E135-00-00,E135-00-00_0007       ,6690.1
    1560    1560
River Rch & RM=E135-00-00,E135-00-00_0007       ,5858.9
    1600    1600
River Rch & RM=E135-00-00,E135-00-00_0007       ,5559
    1650    1650
River Rch & RM=E135-00-00,E135-00-00_0007       ,2496.4
    1669    1669
Boundary for River Rch & Prof#=E135-00-00,E135-00-00_0007       , 1
Up Type= 0
Dn Type= 3
Dn Slope=.00161
Boundary for River Rch & Prof#=E135-00-00,E135-00-00_0007       , 2
Up Type= 0
Dn Type= 1
Dn Known WS=101.75
DSS Import GetInterval= 0
DSS Import GetPeak= 0
DSS Import FillOption= 0

--- E135-00-00.f01 (steady flow) ---

Flow Title=FEMA Effective June 2007
Version=Version 3.0.1  Mar 2001
Number of Profiles= 4
Profile Names=10PCT_10yr, 2PCT_50yr, 1PCT_100yr, 0.2PCT_500yr
River Rch & RM=E135-00-00,E135-00-00_0007       ,9128.3
     680    1010    1220    1720
River Rch & RM=E135-00-00,E135-00-00_0007       ,8955.1
     720    1080    1290    1820
River Rch & RM=E135-00-00,E135-00-00_0007       ,8219.0
     750    1140    1350    1880
River Rch & RM=E135-00-00,E135-00-00_0007       ,7711.8
     760    1150    1360    1900
River Rch & RM=E135-00-00,E135-00-00_0007       ,7579.9
     790    1220    1420    1980
River Rch & RM=E135-00-00,E135-00-00_0007       ,7000.5
     810    1250    1460    2030
River Rch & RM=E135-00-00,E135-00-00_0007       ,6690.1
     870    1360    1560    2150
River Rch & RM=E135-00-00,E135-00-00_0007       ,5858.9
     890    1400    1600    2200
River Rch & RM=E135-00-00,E135-00-00_0007       ,5559
     940    1450    1650    2300
River Rch & RM=E135-00-00,E135-00-00_0007       ,2496.4
     963    1430    1669    2358
Boundary for River Rch & Prof#=E135-00-00,E135-00-00_0007       , 1
Up Type= 0
Dn Type= 3
Dn Slope=.00161
Boundary for River Rch & Prof#=E135-00-00,E135-00-00_0007       , 2
Up Type= 0
Dn Type= 3
Dn Slope=.00161
Boundary for River Rch & Prof#=E135-00-00,E135-00-00_0007       , 3
Up Type= 0
Dn Type= 3
Dn Slope=.00161
Boundary for River Rch & Prof#=E135-00-00,E135-00-00_0007       , 4
Up Type= 0
Dn Type= 3
Dn Slope=.00161
DSS Import GetInterval= 0
DSS Import GetPeak= 0
DSS Import FillOption= 0

--- E135-00-00.f04 (steady flow) ---

Flow Title=Storage Routing
Version=Version 3.0.1  Mar 2001
Number of Profiles= 7
Profile Names=.25x10% flood,.50x10% flood,10% flood,2% flood,1% flood,0.2% flood,1.25x0.2% flood
River Rch & RM=E135-00-00,E135-00-00_0007       ,9128.3
     105     210     420     560     640     895    1119
River Rch & RM=E135-00-00,E135-00-00_0007       ,9076.7
     108     217     434     581     664     929    1161
River Rch & RM=E135-00-00,E135-00-00_0007       ,8219
     119     238     476     642     735    1028    1285
River Rch & RM=E135-00-00,E135-00-00_0007       ,7007.3
     133     266     533     726     833    1164    1455
River Rch & RM=E135-00-00,E135-00-00_0007       ,4823.1
     203     407     590     810     930    1300    1625
River Rch & RM=E135-00-00,E135-00-00_0007       ,2507.1
     158     315     630     860     980    1370    1713
Boundary for River Rch & Prof#=E135-00-00,E135-00-00_0007       , 1
Up Type= 0
Dn Type= 3
Dn Slope=.00161
Boundary for River Rch & Prof#=E135-00-00,E135-00-00_0007       , 2
Up Type= 0
Dn Type= 3
Dn Slope=.00161
Boundary for River Rch & Prof#=E135-00-00,E135-00-00_0007       , 3
Up Type= 0
Dn Type= 3
Dn Slope=.00161
Boundary for River Rch & Prof#=E135-00-00,E135-00-00_0007       , 4
Up Type= 0
Dn Type= 3
Dn Slope=.00161
Boundary for River Rch & Prof#=E135-00-00,E135-00-00_0007       , 5
Up Type= 0
Dn Type= 3
Dn Slope=.00161
Boundary for River Rch & Prof#=E135-00-00,E135-00-00_0007       , 6
Up Type= 0
Dn Type= 3
Dn Slope=.00161
Boundary for River Rch & Prof#=E135-00-00,E135-00-00_0007       , 7
Up Type= 0
Dn Type= 3
Dn Slope=.00161
DSS Import GetInterval= 0
DSS Import GetPeak= 0
DSS Import FillOption= 0

--- E135-00-00.g01 (geometry) ---

Geom Title=E135-00-00 June 2007
Version=Version 3.0.1  Mar 2001

River Reach=E135-00-00      ,E135-00-00_0007
Reach XY= 30
      3046987.65     13889814.71      3047069.25     13889990.93
      3047090.95     13890015.23      3047153.59     13890031.28
      3047922.05     13890053.84      3048047.55     13890084.68
      3048558.29     13890098.04      3049033.66     13890123.74
      3049121.33     13890137.63      3049289.73     13890137.63
      3049511.96     13890117.66      3049590.95     13890096.83
        3050269.       13889793.       3050325.5       13889777.
        3050431.       13889770.      3050648.24     13889781.73
      3050751.54     13889773.91      3050868.73      13889744.4
      3050970.29     13889695.79       3051956.4     13889087.28
      3052061.43     13889045.62        3052178.       13889016.
      3052390.43     13889002.21      3052554.49     13889010.89
      3052736.78     13889000.48      3052821.85     13889004.82
      3052949.46     13889031.73       3054078.8     13889079.47
      3054182.09     13889094.56       3055850.5     13889156.73

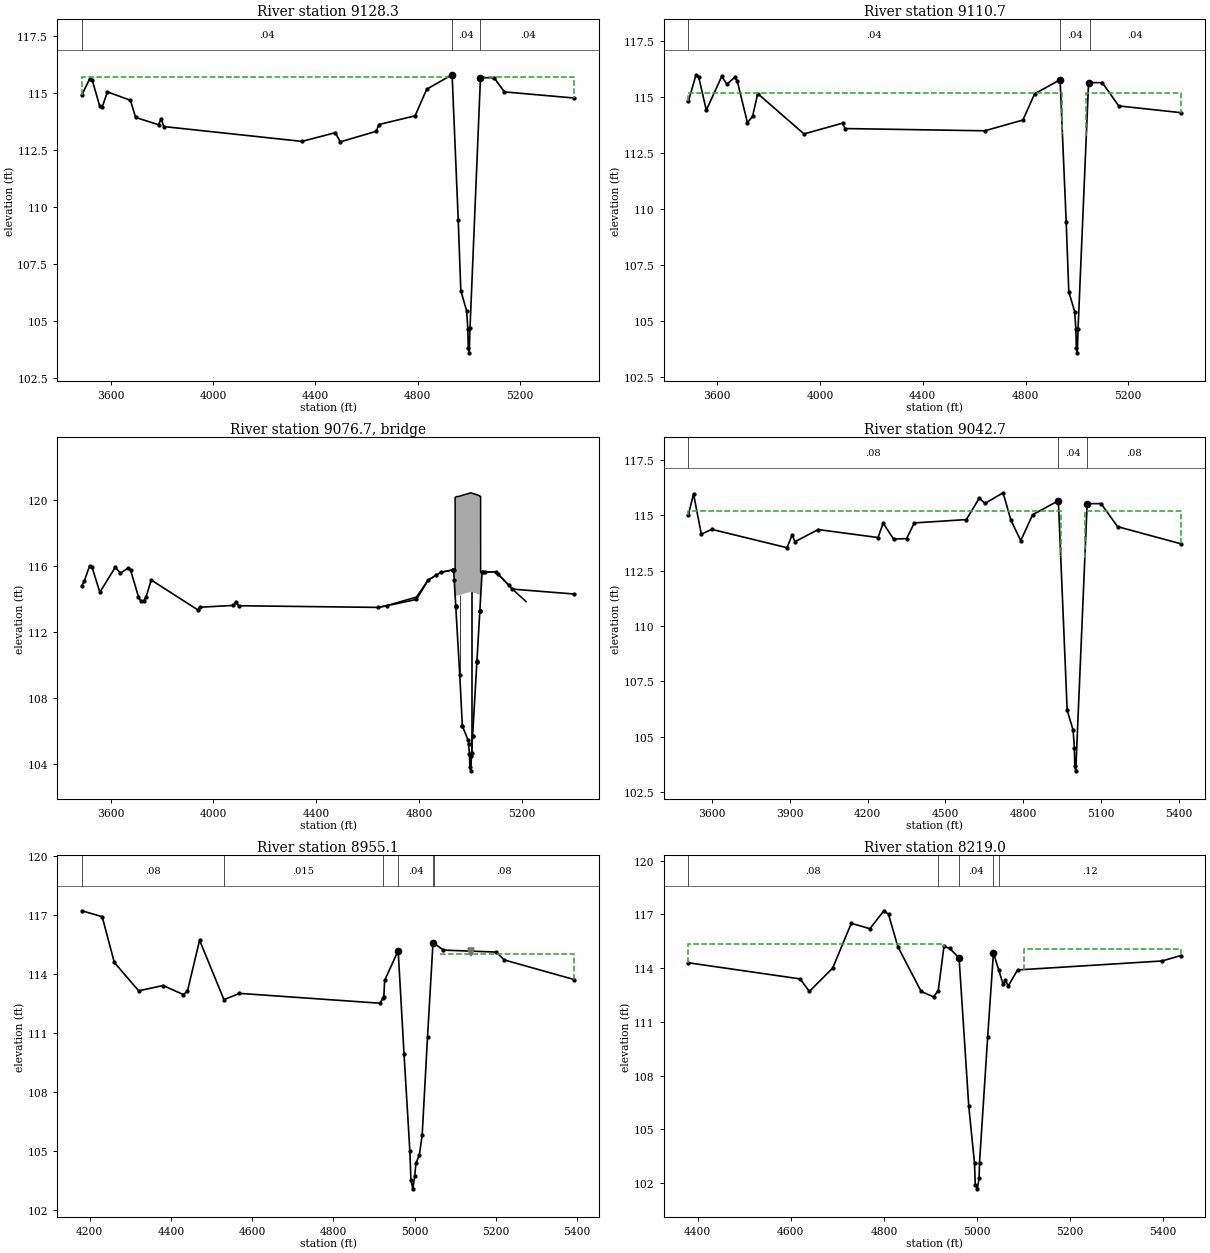
Type RM Length L Ch R = 1 ,9128.3  ,9.6,17.6,10.3
BEGIN DESCRIPTION:
Hempstead Road - 4
Formerly Cross Section E135-00-00-X12
***Ineffective area in the left overbank indicates ponding water***
***Ineffective area in the right overbank per mapping indicates back-up water from downstream low right bank approx. 185' upstream of X10.***
END DESCRIPTION:
XS GIS Cut Line= 4
       3045892.3      13890923.7      3046763.46      13890171.6
      3047359.63     13889708.31      3047373.62     13889696.08
#Sta/Elev= 30
  3487.7   114.9  3517.7  115.59  3527.7  115.57  3557.7   114.4  3567.7  114.38
  3587.7  115.03  3677.7  114.66  3697.7  113.91  3787.7  113.59  3797.7  113.86
  3807.7  113.51  4347.7  112.86  4477.7  113.24  4497.7  112.84  4637.7   113.3
  4648.6   113.6  4789.9  113.98  4835.5  115.15  4934.6  115.78  4958.5  109.41
  4968.6  106.32  4991.3  105.43  4996.1  104.64  4997.8   103.8  5001.5  103.59
  5004.5  104.67  5045.4  115.65  5098.9  115.65  5138.6  115.03  5412.2  114.76
#Mann= 3 ,-1 , 0
  3487.7     .04       0  4934.6     .04       0  5045.4     .04       0
#XS Ineff= 2 , 0
       0    4929   115.7    5049       0   115.7
Permanent Ineff=
       F       F
Bank Sta=4934.6,5045.4
XS Rating Curve= 0
Exp/Cntr=.5,.3

Type RM Length L Ch R = 1 ,9110.7  ,67.7,68,69
BEGIN DESCRIPTION:
Hempstead Road - 3
***Ineffective area in the left overbank indicates ponding water***
***Ineffective area in the right overbank per mapping indicates back-up water from downstream low right bank approx. 185' upstream of X10.***
END DESCRIPTION:
XS GIS Cut Line= 5
       3045898.9      13890934.9      3046772.68     13890177.24
      3046990.85     13890006.71      3047145.04     13889888.91
      3047370.69     13889708.87
#Sta/Elev= 30
  3488.1  114.81  3518.1     116  3528.1  115.92  3558.1  114.42  3618.1  115.93
  3638.1  115.58  3668.1  115.88  3678.1  115.74  3718.1  113.86  3738.1  114.14
  3758.1  115.16  3938.1  113.36  4088.1  113.84  4098.1   113.6  4641.6   113.5
  4789.9  113.98  4835.5  115.15  4934.6  115.78  4958.4  109.41  4968.5  106.32
  4991.3  105.43  4996.1  104.64  4997.8   103.8  5001.5  103.59  5004.5  104.67
  5045.4  115.65  5050.6  115.65  5098.9  115.65  5162.6  114.61  5404.2  114.31
#Mann= 3 ,-1 , 0
  3488.1     .04       0  4934.6     .04       0  5050.6     .04       0
#XS Ineff= 2 , 0
       0 4943.59   115.2 5036.52       0   115.2
Permanent Ineff=
       F       F
Bank Sta=4934.6,5045.4
XS Rating Curve= 0
Exp/Cntr=.5,.3

Type RM Length L Ch R = 3 ,9076.7  ,,,
BEGIN DESCRIPTION:
HEMPSTEAD ROAD
Structure ID: E135-00-00-06
END DESCRIPTION:
Bridge Culvert--1,0,-1,-1, 0
Deck Dist Width WeirC Skew NumUp NumDn MinLoCord MaxHiCord MaxSubmerge Is_Ogee
10,48,2.6,0, 43, 43, , , .95, 0, ,,,
  4641.6  4676.6  4789.9  4835.5  4865.9    4884 4931.39  4940.4  4940.5 4940.61
 4943.52  4943.6    4946  4951.8 4951.91    4952  4967.4  4977.5  4977.6  5000.3
  5001.6  5005.1  5006.8  5010.5  5012.9  5013.5  5017.3  5017.4 5033.99  5034.1
 5036.52  5036.6  5036.7 5039.62  5039.7  5045.4  5050.6    5055  5098.9  5106.7
  5148.1  5162.6  5216.4
   113.5  113.62  114.13  115.16  115.45  115.63  115.78  115.78  120.17  120.17
   120.2   120.2  120.22  120.22  120.22  120.22  120.29  120.34  120.34  120.44
  120.45  120.43  120.42   120.4  120.39  120.39  120.37  120.37  120.28  120.28
  120.24  120.24  120.21  120.23  115.64  115.66  115.66  115.66  115.66  115.53
  114.87  114.62  113.85
                                                                                
           114.2  114.22  114.22  114.22  114.22  114.29  114.34  114.34  114.44
  114.45  114.43  114.42   114.4  114.39  114.39  114.37  114.37  114.28  114.28
  114.22
                        
  4641.6  4676.6  4789.9  4835.5  4865.9    4884 4931.39  4940.4  4940.5 4940.61
 4943.52  4943.6    4946  4951.8 4951.91    4952  4967.4  4977.5  4977.6  5000.3
  5001.6  5005.1  5006.8  5010.5  5012.9  5013.5  5017.3  5017.4 5033.99  5034.1
 5036.52  5036.6  5036.7 5039.62  5039.7  5045.4  5050.6    5055  5098.9  5106.7
  5148.1  5162.6  5216.4
   113.5  113.62  114.13  115.16  115.45  115.63  115.78  115.78  120.17  120.17
   120.2   120.2  120.22  120.22  120.22  120.22  120.29  120.34  120.34  120.44
  120.45  120.43  120.42   120.4  120.39  120.39  120.37  120.37  120.28  120.28
  120.24  120.24  120.21  120.23  115.64  115.66  115.66  115.66  115.66  115.53
  114.87  114.62  113.85
                                                                                
           114.2  114.22  114.22  114.22  114.22  114.29  114.34  114.34  114.44
  114.45  114.43  114.42   114.4  114.39  114.39  114.37  114.37  114.28  114.28
  114.22
                        
Pier Skew, UpSta & Num, DnSta & Num=  ,4958.5, 2 ,4958.5, 2 , 0 , 0 , 0 ,,
     1.3     1.3
  108.18  115.29
     1.3     1.3
   108.1  115.21
Pier Skew, UpSta & Num, DnSta & Num=  ,5004.5, 2 ,5004.5, 2 , 0 , 0 , 0 ,,
     1.3     1.3
  103.45  115.39
     1.3     1.3
  103.37  115.31
BR Coef= 1 , 1 , 1 ,1.25, 0 ,,,.8,-1,2,0,
WSPro=,,,, 1 ,,,, 0 ,,,, 0 ,,,,-1 ,-1 ,-1 , 0 , 0 , 0 , 0 , 0
BR U #Sta/Elev= 59
  3488.1  114.81  3498.1  115.13  3518.1     116  3528.1  115.92  3558.1  114.42
  3618.1  115.93  3638.1  115.58  3668.1  115.88  3678.1  115.74  3708.1  114.16
  3718.1  113.86  3728.1  113.88  3738.1  114.14  3758.1  115.16  3938.1  113.36
  3948.1  113.51  4078.1  113.62  4088.1  113.84  4098.1   113.6  4641.6   113.5
  4676.6  113.61  4789.9  113.98  4835.5  115.15  4865.9  115.44    4884  115.62
 4931.39  115.77  4931.5  115.77 4931.61  115.77  4934.6  115.78    4937  115.14
  4942.8  113.59 4942.91  113.56    4943  113.53  4958.4  109.41  4968.5  106.32
  4968.6  106.32  4991.3  105.43  4992.6  105.22  4996.1  104.64  4997.8   103.8
  5001.5  103.59  5003.9  104.47  5004.5  104.67  5008.3  105.68  5008.4  105.71
 5024.99  110.17  5025.1   110.2 5025.21  110.23 5036.49  113.26  5036.6  113.29
  5036.7  113.31  5045.4  115.65  5050.6  115.65    5055  115.65  5098.9  115.65
  5106.7  115.52  5148.1  114.86  5162.6  114.61  5404.2  114.31
BR U #Mann= 3
  3488.1     .04  4934.6     .03  5050.6     .04
BR D #Sta/Elev= 63
  3510.3     115  3520.3  115.63  3530.3  115.96  3560.3  114.14  3590.3  114.05
  3600.3  114.36  3890.3  113.53  3910.3  114.12  3920.3   113.8  4010.3  114.35
  4030.3  114.09  4240.3  113.99  4250.3  114.43  4260.3  114.64  4300.3  113.92
  4350.3  113.94  4380.3  114.65  4400.3  114.39  4580.3   114.8  4600.3  115.41
  4610.3  115.45  4630.3  115.77  4651.9  115.53  4721.9  116.01  4751.9  114.77
  4789.9  113.85  4835.5  115.02  4865.9  115.31    4884  115.49 4931.39  115.64
  4931.5  115.64 4931.61  115.64  4934.6  115.65    4937  115.01  4942.8  113.46
 4942.91  113.43    4943   113.4  4958.4  109.28  4968.5  106.19  4968.6  106.19
  4991.3   105.3  4992.6  105.09  4996.1  104.51  4997.8  103.67  5001.5  103.46
  5003.9  104.34  5004.5  104.54  5008.3  105.55  5008.4  105.58 5024.99  110.04
  5025.1  110.07 5025.21   110.1 5036.49  113.13  5036.6  113.16  5036.7  113.18
  5045.4  115.52  5050.6  115.52    5055  115.52  5098.9  115.52  5106.7  115.39
  5148.1  114.73  5162.6  114.48  5405.8  113.71
BR D #Mann= 3
  3510.3     .08  4934.6     .03  5045.4     .08
BC Design=,, 0 ,, 0 ,,,,,,

Type RM Length L Ch R = 1 ,9042.7  ,132,87.6,57.1
BEGIN DESCRIPTION:
Hempstead Road - 2
***Ineffective area in the left overbank indicates ponding water***
***Ineffective area in the right overbank per mapping indicates back-up water from downstream low right bank approx. 185' upstream of X10.***
END DESCRIPTION:
XS GIS Cut Line= 3
      3045953.54       13890977.      3046818.03     13890231.56
      3047406.54      13889760.3
#Sta/Elev= 30
  3510.3     115  3530.3  115.96  3560.3  114.14  3600.3  114.36  3890.3  113.53
  3910.3  114.12  3920.3   113.8  4010.3  114.35  4240.3  113.99  4260.3  114.64
  4300.3  113.92  4350.3  113.94  4380.3  114.65  4580.3   114.8  4630.3  115.77
  4651.9  115.53  4721.9  116.01  4751.9  114.77  4789.9  113.85  4835.5  115.02
  4934.6  115.65  4968.5  106.19  4991.3   105.3  4996.1  104.51  4997.8  103.67
  5001.5  103.46  5045.4  115.52  5098.9  115.52  5162.6  114.48  5405.8  113.71
#Mann= 3 ,-1 , 0
  3510.3     .08       0  4934.6     .04       0  5045.4     .08       0
#XS Ineff= 2 , 0
       0 4943.59   115.2 5036.52       0   115.2
Permanent Ineff=
       F       F
Bank Sta=4934.6,5045.4
XS Rating Curve= 0
Exp/Cntr=.5,.3

Type RM Length L Ch R = 1 ,8955.1  ,738.6,736.1,733.7
BEGIN DESCRIPTION:
Hempstead Road - 1
Formerly Cross Section E135-00-00-X11
Located At: DS HWY290
***Ineffective area in the left overbank indicates ponding water***
***Ineffective area in the right overbank per mapping indicates back-up water from downstream low right bank approx. 185' upstream of X10.***
END DESCRIPTION:
XS GIS Cut Line= 5
      3047141.26      13890852.7      3047162.65      13890452.2
      3047174.62     13890159.78      3047187.63     13889963.54
      3047425.58     13889745.77
#Sta/Elev= 30
  4180.5   117.2  4230.5   116.9  4260.5  114.57  4320.5  113.13  4380.5   113.4
  4430.5  112.94  4440.5  113.11  4470.5   115.7  4530.5  112.68  4568.7     113
  4914.2   112.5  4922.5  112.75  4924.2   112.8  4926.3  113.66  4959.6  115.17
    4974  109.93  4988.4  104.98    4991  103.52  4995.7  103.06  5000.4  103.71
  5003.3  104.36  5011.7  104.78  5018.7  105.78  5031.9  110.78  5045.4  115.58
  5047.7  115.55  5070.9   115.2  5200.9   115.1  5220.9   114.7  5393.5   113.7
#Mann= 6 ,-1 , 0
  4180.5     .08       0  4530.5    .015       0  4922.5     .04       0
  4959.6     .04       0  5045.4     .04       0  5047.7     .08       0
Levee=0,,,-1,5138.85,115.03,,
#XS Ineff= 2 , 0
         4952.84  114.26 5062.88             115
Permanent Ineff=
       F       F
Bank Sta=4959.6,5045.4
XS Rating Curve= 0
Exp/Cntr=.3,.1

Type RM Length L Ch R = 1 ,8219.0  ,407.1,408.6,407.3
BEGIN DESCRIPTION:
Cross Section E135-00-00-X10
Located At: 2ND US STEEPLE WAY
***Ineffective area in the right and left overbanks indicates ponding water***
END DESCRIPTION:
XS GIS Cut Line= 4
     3047919.282      13890673.7      3047918.06     13890147.23
      3047918.96     13889996.68      3047919.05     13889616.13
#Sta/Elev= 30
  4379.9   114.3  4619.9   113.4  4639.9   112.7  4689.9     114  4729.9   116.5
  4769.9   116.2  4799.9   117.2  4809.9     117  4829.9   115.2  4879.9   112.7
  4906.5   112.4  4916.7  112.75  4928.9  115.21  4941.5   115.1  4961.4  114.57
  4982.2   106.3  4994.6  103.11  4996.2  101.93  5000.6  101.69  5004.4  102.29
  5005.3  103.14  5022.8  110.15  5035.2  114.86  5046.4  113.91  5055.8  113.11
  5060.9  113.33    5067     113    5087   113.9    5397   114.4  5437.6   114.7
#Mann= 5 ,-1 , 0
  4379.9     .08       0  4916.7     .04       0  4961.4     .04       0
  5035.2     .04       0  5046.4     .12       0
#XS Ineff= 2 , 0
         4929.26  115.33 5100.09          115.07
Permanent Ineff=
       F       F
Bank Sta=4961.4,5035.2
XS Rating Curve= 0
Exp/Cntr=.3,.1

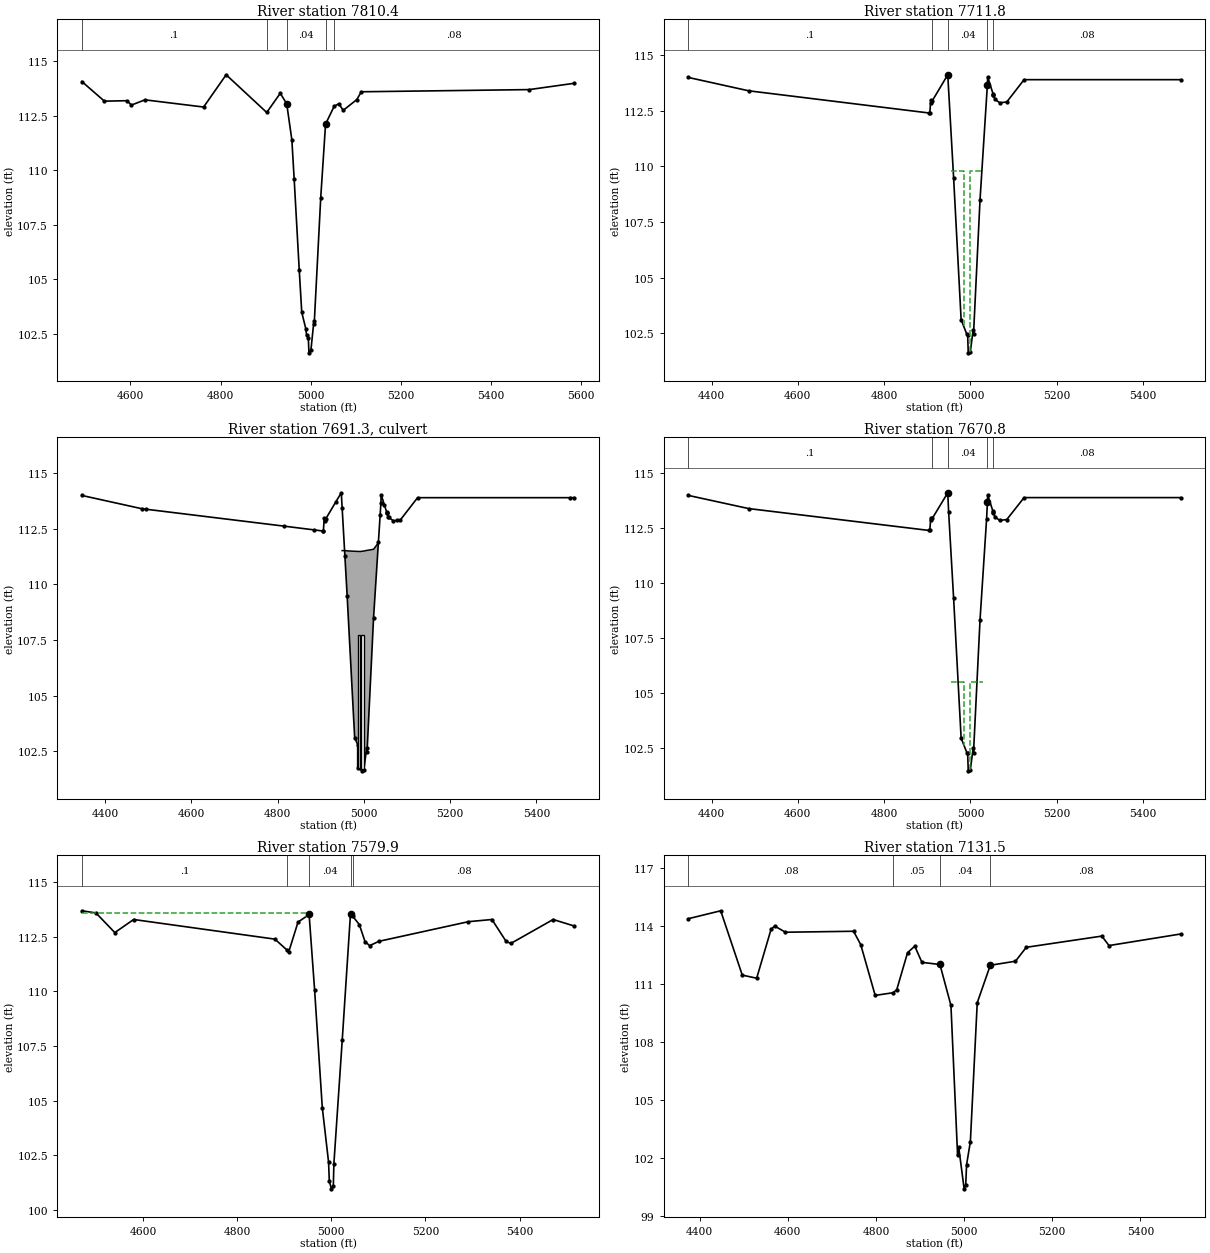
Type RM Length L Ch R = 1 ,7810.4  ,98.4,98.6,100
BEGIN DESCRIPTION:
W of Steeple Way - 4
Interpolated channel, LIDAR overbanks
END DESCRIPTION:
XS GIS Cut Line= 4
      3048274.67      13890597.1      3048320.61     13890145.19
      3048322.84     13890049.77      3048324.67      13889507.4
#Sta/Elev= 30
  4492.5  114.08  4542.5  113.18  4592.5   113.2  4602.5     113  4632.5  113.24
  4762.5  112.91  4812.5  114.39  4902.5  112.66  4932.5  113.54  4946.8  113.06
 4958.22   111.4 4963.34   109.6 4974.55  105.44 4980.15  103.49 4989.06  102.74
 4990.94  102.43 4994.74   102.3 4996.09  101.63 5000.49  101.76    5007  103.07
 5007.77  102.96 5022.22  108.75 5032.94  112.13  5052.2  112.95  5062.2  113.06
  5072.2  112.76  5102.2  113.25  5112.2  113.61  5484.6  113.71  5584.6     114
#Mann= 5 ,-1 , 0
  4492.5      .1       0  4902.5     .04       0  4946.8     .04       0
 5032.94     .04       0  5052.2     .08       0
Bank Sta=4946.8,5032.94
XS Rating Curve= 0
Exp/Cntr=.5,.3

Type RM Length L Ch R = 1 ,7711.8  ,40.7,41,40.5
BEGIN DESCRIPTION:
W of Steeple Way - 3
Formerly E135-00-00-05
END DESCRIPTION:
XS GIS Cut Line= 5
      3048360.02      13890746.2      3048374.16      13890607.2
      3048420.49      13890151.4      3048422.84      13890051.1
      3048424.34      13889607.7
#Sta/Elev= 27
  4346.1     114  4485.9   113.4  4905.1   112.4  4905.9   112.4  4908.1  112.99
    4909  112.87  4911.6  112.95  4947.5  114.12  4961.1  109.48  4978.5  103.11
  4991.8  102.45  4993.6  102.43    4995  101.62  4999.6  101.64  5006.4  102.65
  5007.2  102.45  5022.3   108.5  5039.4  113.68    5040  114.03    5053  113.23
  5053.3  113.21  5053.4  113.27  5056.4  113.02  5068.3  112.86  5084.4   112.9
  5124.4   113.9  5487.7   113.9
#Mann= 5 ,-1 , 0
  4346.1      .1       0  4911.6     .04       0  4947.5     .04       0
  5039.4     .04       0    5053     .08       0
#XS Ineff= 4 ,-1
    4347    4945   113.9    4956  4985.5   109.8  4999.4    5030   109.8
    5042    5486   113.8
Permanent Ineff=
       F       F       F       F
Bank Sta=4947.5,5039.4
XS Rating Curve= 0
Exp/Cntr=.5,.3

Type RM Length L Ch R = 2 ,7691.3  ,,,
BEGIN DESCRIPTION:
W OF STEEPLE WAY
Structure ID: E135-00-00-05
***Ineffective area in the right and left overbanks indicates ponding water***
END DESCRIPTION:
Bridge Culvert--1,0,-1,-1, 0
Deck Dist Width WeirC Skew NumUp NumDn MinLoCord MaxHiCord MaxSubmerge Is_Ogee
10,21,3,0, 13, 13, , , .95, 0, ,,,
  4949.5  4955.8  4961.1  4978.5  4991.8  4992.3  4993.6    4995  4999.6  5006.4
  5007.2  5022.3  5034.5
  111.52  111.52  111.51  111.49  111.48  111.48  111.49  111.49   111.5  111.53
  111.53  111.58   111.9
                                                                                
                        
  4949.5  4955.8  4961.1  4978.5  4991.8  4992.3  4993.6    4995  4999.6  5006.4
  5007.2  5022.3  5034.5
  111.52  111.52  111.51  111.49  111.48  111.48  111.49  111.49   111.5  111.53
  111.53  111.58   111.9
                                                                                
                        
BR Coef= 1 , 1 , 0 ,1.25, 0 ,,,.8,0,2,0,
WSPro=,,,, 1 ,,,, 0 ,,,, 0 ,,,,-1 ,-1 ,-1 , 0 , 0 , 0 , 0 , 0
Culvert=2,6,6,21,.015,.4,1,8,1,101.74,4988.5,101.72,4988.5,Culvert #1  , 0 ,10
Culvert Bottom n=.02
Culvert=2,6,6,21,.015,.4,1,8,1,101.72,4996.4,101.73,4996.4,Culvert #2  , 0 ,10
Culvert Bottom n=.02
BR U #Sta/Elev= 45
  4346.1     114  4485.9   113.4  4495.1  113.38  4815.1  112.62  4885.1  112.45
  4905.1   112.4  4905.9   112.4  4908.1  112.99    4909  112.87  4911.6  112.95
  4935.1  113.72  4947.5  114.12  4949.5  113.44  4955.8  111.29  4961.1  109.48
  4978.5  103.11 4985.49   102.8  4985.5  101.74 4991.49  101.74  4991.5   102.3
  4991.8  102.45  4992.3  102.43 4993.35  102.43  4993.4  101.74    4995  101.62
  4999.6  101.64  5006.4  102.65  5007.2  102.45  5022.3   108.5  5033.5  111.89
  5037.5   113.1  5039.4  113.68    5040  114.03  5047.5  113.57    5053  113.23
  5053.3  113.21  5053.4  113.27  5056.4  113.02  5057.5  113.01  5068.3  112.86
  5077.5  112.88  5084.4   112.9  5124.4   113.9  5476.6   113.9  5487.7   113.9
BR U #Mann= 5
  4346.1      .1  4911.6     .04  4947.5     .04  5039.4     .04    5053     .08
BR D #Sta/Elev= 46
  4346.1     114  4485.9   113.4  4495.1  113.38  4815.1  112.62  4885.1  112.45
  4905.1   112.4  4905.9   112.4  4908.1  112.99    4909  112.87  4911.6  112.95
  4935.1  113.72  4947.5  114.12  4949.5  113.26  4955.8  111.11  4961.1   109.3
  4978.5  102.93 4985.49   102.7  4985.5  101.72 4991.49  101.72  4991.5   102.3
  4991.8  102.27  4992.3  102.25 4993.35   102.3  4993.4  101.72  4993.6  101.72
    4995  101.44  4999.6  101.46  5006.4  102.47  5007.2  102.27  5022.3  108.32
  5033.5  111.71  5037.5  112.92  5039.4  113.68    5040  114.03  5047.5  113.57
    5053  113.23  5053.3  113.21  5053.4  113.27  5056.4  113.02  5057.5  113.01
  5068.3  112.86  5077.5  112.88  5084.4   112.9  5124.4   113.9  5476.6   113.9
  5487.7   113.9
BR D #Mann= 5
  4346.1      .1  4911.6     .04  4947.5     .04  5039.4     .04    5053     .08
BC Design=,, 0 ,, 0 ,,,,,,

Type RM Length L Ch R = 1 ,7670.8  ,89.5,90.9,90.8
BEGIN DESCRIPTION:
W of Steeple Way - 2
Formerly E135-00-00-05
END DESCRIPTION:
XS GIS Cut Line= 4
      3048401.62      13890752.2      3048416.45      13890604.9
      3048460.96     13890162.76      3048472.83     13889613.74
#Sta/Elev= 29
  4346.1     114  4485.9   113.4  4905.1   112.4  4905.9   112.4  4908.1  112.99
    4909  112.87  4911.6  112.95  4947.5  114.12  4949.5  113.26  4961.1   109.3
  4978.5  102.93  4991.8  102.27  4993.6  102.25    4995  101.44  4999.6  101.46
  5006.4  102.47  5007.2  102.27  5022.3  108.32  5037.5  112.92  5039.4  113.68
    5040  114.03    5053  113.23  5053.3  113.21  5053.4  113.27  5056.4  113.02
  5068.3  112.86  5084.4   112.9  5124.4   113.9  5487.7   113.9
#Mann= 5 ,-1 , 0
  4346.1      .1       0  4911.6     .04       0  4947.5     .04       0
  5039.4     .04       0    5053     .08       0
#XS Ineff= 4 ,-1
    4347    4945   113.9    4956  4985.5   105.5  4999.4    5030   105.5
    5042    5486   113.8
Permanent Ineff=
       F       F       F       F
Bank Sta=4947.5,5039.4
XS Rating Curve= 0
Exp/Cntr=.5,.3

Type RM Length L Ch R = 1 ,7579.9  ,491.4,448.4,414.8
BEGIN DESCRIPTION:
W of Steeple Way - 1
Formerly Cross Section E135-00-00-X09
Located At: US STEEPLE WAY
***Ineffective area in the right and left overbanks indicates ponding water***
END DESCRIPTION:
XS GIS Cut Line= 4
      3048491.96     13890623.97      3048549.54     13890176.47
      3048556.57     13889996.76       3048529.6     13889582.68
#Sta/Elev= 29
  4470.3   113.7  4500.3   113.6  4540.3   112.7  4580.3   113.3  4880.3   112.4
    4907  111.88  4909.8  111.82  4929.4  113.18    4953  113.53  4964.6  110.09
    4981  104.67  4994.3  102.18  4995.9   101.3  5000.4  100.95  5004.4  101.06
  5005.6   102.1  5023.4  107.79  5040.9  113.57  5045.2  113.46  5059.6  113.07
  5071.7  112.29  5081.5   112.1  5101.3   112.3  5291.3   113.2  5341.3   113.3
  5371.3   112.3  5381.3   112.2  5471.3   113.3  5516.3     113
#Mann= 5 ,-1 , 0
  4470.3      .1       0    4907     .04       0    4953     .04       0
  5040.9     .04       0  5045.2     .08       0
#XS Ineff= 2 , 0
         4946.03   113.6 5064.45          112.66
Permanent Ineff=
       F       F
Bank Sta=4953,5040.9
XS Rating Curve= 0
Exp/Cntr=.3,.1

Type RM Length L Ch R = 1 ,7131.5  ,124.6,131,131.1
BEGIN DESCRIPTION:
Steeple Way - 4
Interpolated channel, LIDAR overbanks
END DESCRIPTION:
XS GIS Cut Line= 3
       3049380.9       13890780.      3049264.96     13890482.47
      3048643.77      13889636.6
#Sta/Elev= 30
 4374.27  114.37 4447.72  114.78 4496.69  111.45 4529.33  111.29 4561.98  113.82
 4570.14  113.99 4594.62  113.67  4749.2  113.72 4765.52  113.02 4798.17   110.4
 4838.98  110.54 4847.14   110.7 4871.62  112.61 4887.95  112.95 4904.27  112.11
 4945.07     112 4970.06  109.88 4985.14  102.12 4987.57  102.56    5000  100.39
  5003.6   100.6 5005.52  101.64 5014.13  102.83  5029.7  110.02 5059.33  111.96
 5116.46  112.17 5140.95  112.89 5312.34  113.47 5328.66  112.98 5491.48  113.58
#Mann= 4 ,-1 , 0
 4374.27     .08       0 4838.98     .05       0 4945.07     .04       0
 5059.33     .08       0
Bank Sta=4945.07,5059.33
XS Rating Curve= 0
Skew Angle= 35.3
Exp/Cntr=.5,.3

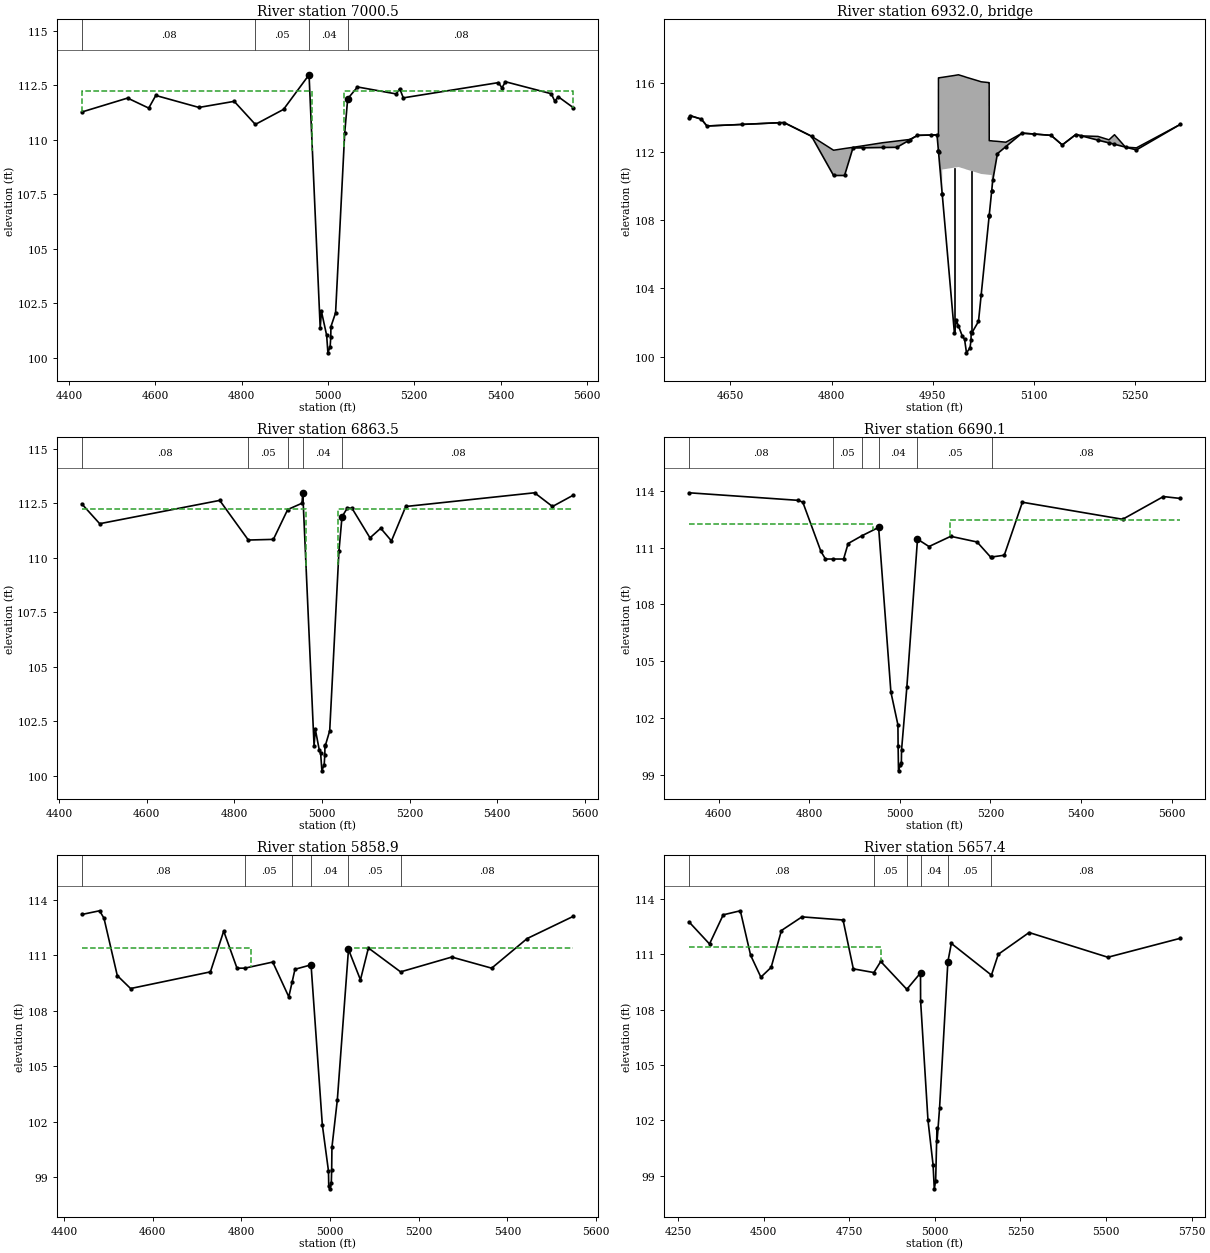
Type RM Length L Ch R = 1 ,7000.5  ,129.4,137,134.7
BEGIN DESCRIPTION:
Steeple Way - 3
Formerly E135-00-00-04
END DESCRIPTION:
XS GIS Cut Line= 3
      3049474.08      13890743.7      3049353.35      13890433.8
      3048724.36      13889577.4
#Sta/Elev= 30
 4429.88  111.28 4535.97  111.92 4584.94  111.46 4601.27  112.04 4701.32  111.49
 4782.94  111.77  4831.9  110.71  4897.2   111.4 4956.37  112.99 4982.16  101.37
 4985.09  102.12 4997.17  101.02 5000.03  100.22 5005.25  100.51 5006.72  100.96
 5006.97  101.42 5017.82  102.06 5038.96  110.32  5045.9  111.89 5068.58  112.43
 5158.36  112.11 5166.52  112.35 5174.68  111.93 5395.04  112.63  5403.2  112.39
 5411.36  112.67 5517.46  112.12 5525.62  111.78 5533.78  111.98 5568.55  111.48
#Mann= 4 ,-1 , 0
 4429.88     .08       0  4831.9     .05       0 4956.37     .04       0
  5045.9     .08       0
#XS Ineff= 2 , 0
   921.3 4964.12  112.23 5037.33   921.3  112.23
Permanent Ineff=
       F       F
Bank Sta=4956.37,5045.9
XS Rating Curve= 0
Skew Angle= 35.3
Exp/Cntr=.5,.3

Type RM Length L Ch R = 3 ,6932.0  ,,,
BEGIN DESCRIPTION:
STEEPLE WAY
Structure ID: E135-00-00-04
END DESCRIPTION:
Bridge Culvert--1,0,-1,-1, 0
Deck Dist Width WeirC Skew NumUp NumDn MinLoCord MaxHiCord MaxSubmerge Is_Ogee
10,117,2.6,35.3, 56, 56, , , .95, 0, ,,,
  4588.7  4590.8 4607.14  4615.3 4666.64 4721.56 4729.56 4770.37 4803.01 4819.34
 4831.74 4846.68 4875.81 4896.87  4913.6 4916.21 4927.39 4947.72 4956.35  4958.4
 4958.49 4958.58 4964.05  4964.1 4982.16 4985.09 4988.11 4993.91 4997.17 5000.03
 5005.25 5006.72 5006.97  5007.7 5017.82 5021.74 5033.56 5033.65 5033.74 5037.34
 5037.41 5038.96  5045.9 5058.38  5082.5 5100.25 5125.47 5141.96 5162.11 5170.44
 5194.92 5211.25 5219.41 5235.73 5251.89 5317.18
  113.95  114.11  113.91  113.51   113.6   113.7  113.71  112.91  112.09  112.19
  112.26  112.35  112.53  112.63  112.71  112.72  112.96  112.98  112.99  112.93
  116.33  116.33  116.36  116.36  116.47  116.49  116.51  116.44   116.4  116.36
   116.3  116.28  116.28  116.27  116.15   116.1  116.05  116.05  112.65  112.64
  112.64  112.63  112.61  112.56  113.09  113.04  112.96   112.4  113.01  112.93
   112.9   112.7     113  112.27  112.23  113.61
                                                                                
                                                                                
                          110.96  111.07  111.09  111.11  111.04     111  110.96
   110.9  110.88  110.88  110.87  110.75   110.7  110.65  110.65  110.65  110.64
                                                                                
                                                
  4588.7  4590.8 4607.14  4615.3 4666.64 4721.56 4729.56 4770.37 4803.01 4819.34
 4831.74 4846.68 4875.81 4896.87  4913.6 4916.21 4927.39 4947.72 4956.35  4958.4
 4958.49 4958.58 4964.05  4964.1 4982.16 4985.09 4988.11 4993.91 4997.17 5000.03
 5005.25 5006.72 5006.97  5007.7 5017.82 5021.74 5033.56 5033.65 5033.74 5037.34
 5037.41 5038.96  5045.9 5058.38  5082.5 5100.25 5125.47 5141.96 5162.11 5170.44
 5194.92 5211.25 5219.41 5235.73 5251.89 5317.18
  113.95  114.11  113.91  113.51   113.6   113.7  113.71  112.91  112.09  112.19
  112.26  112.35  112.53  112.63  112.71  112.72  112.96  112.98  112.99  112.93
  116.33  116.33  116.36  116.36  116.47  116.49  116.51  116.44   116.4  116.36
   116.3  116.28  116.28  116.27  116.15   116.1  116.05  116.05  112.65  112.64
  112.64  112.63  112.61  112.56  113.09  113.04  112.96   112.4  113.01  112.93
   112.9   112.7     113  112.27  112.23  113.61
                                                                                
                                                                                
                          110.96  111.07  111.09  111.11  111.04     111  110.96
   110.9  110.88  110.88  110.87  110.75   110.7  110.65  110.65  110.65  110.64
                                                                                
                                                
Pier Skew, UpSta & Num, DnSta & Num=  ,4982.156, 2 ,4982.156, 2 , 0 , 0 , 0 ,,
     1.3     1.3
   100.5  112.07
     1.3     1.3
   100.3  111.87
Pier Skew, UpSta & Num, DnSta & Num=  ,5006.967, 2 ,5006.967, 2 , 0 , 0 , 0 ,,
     1.3     1.3
   99.86  111.88
     1.3     1.3
   99.66  111.68
BR Coef= 1 , 1 , 1 ,1.25, 0 ,,,.8,0,2,0,
WSPro=,,,, 1 ,,,, 0 ,,,, 0 ,,,,-1 ,-1 ,-1 , 0 , 0 , 0 , 0 , 0
BR U #Sta/Elev= 56
  4588.7  113.95 4590.82  114.11 4607.14  113.91  4615.3  113.51 4666.64   113.6
 4721.56   113.7 4729.56  113.71 4770.37  112.91 4803.01  110.61 4819.34  110.61
 4831.74  112.22 4846.68  112.23 4875.81  112.25 4896.87  112.26  4913.6  112.64
 4916.21   112.7 4927.39  112.96 4947.72  112.98 4956.37  112.99  4958.4  112.07
 4958.49  112.03 4958.58  111.99 4964.05  109.53 4964.12   109.5 4982.16  101.37
 4985.09  102.12 4988.11   101.8 4993.91  101.19 4997.17  101.02 5000.03  100.22
 5005.25  100.51 5006.72  100.96 5006.97  101.42  5007.7  101.37 5017.82  102.06
 5021.74  103.59 5033.56  108.21 5033.65  108.25 5033.74  108.28 5037.32  109.68
 5037.41  109.71 5038.96  110.32  5045.9  111.89 5058.38   112.3  5082.3  113.09
 5100.25  113.04 5125.47  112.96 5141.96   112.4 5162.11  113.01 5170.44  112.93
 5194.92  112.68 5211.25  112.52 5219.41  112.44 5235.73  112.27 5251.89  112.11
 5317.18  113.61
BR U #Mann= 5
  4588.7     .08 4846.68     .05 4916.21     .04 4956.37     .03  5045.9     .08
BR U Banks=4956.37,5045.9
BR D #Sta/Elev= 56
  4588.7  113.95 4590.82  114.11 4607.14  113.91  4615.3  113.51 4666.64   113.6
 4721.56   113.7 4729.56  113.71 4770.37  112.91 4803.01  110.61 4819.34  110.61
 4831.74  112.22 4846.68  112.23 4875.81  112.25 4896.87  112.26  4913.6  112.64
 4916.21   112.7 4927.39  112.96 4947.72  112.98 4956.37  112.99  4958.4  112.07
 4958.49  112.03 4958.58  111.99 4964.05  109.53 4964.12   109.5 4982.16  101.37
 4985.09  102.12 4988.11   101.8 4993.91  101.19 4997.17  101.02 5000.03  100.22
 5005.25  100.51 5006.72  100.96 5006.97  101.42  5007.7  101.37 5017.82  102.06
 5021.74  103.59 5033.56  108.21 5033.65  108.25 5033.74  108.28 5037.32  109.68
 5037.41  109.71 5038.96  110.32  5045.9  111.89 5058.38   112.3  5082.3  113.09
 5100.25  113.04 5125.47  112.96 5141.96   112.4 5162.11  113.01 5170.44  112.93
 5194.92  112.68 5211.25  112.52 5219.41  112.44 5235.73  112.27 5251.89  112.11
 5317.18  113.61
BR D #Mann= 5
  4588.7     .08 4846.68     .05 4916.21     .04 4956.37     .03  5045.9     .08
BR D Banks=4956.37,5045.9
BC Design=,, 0 ,, 0 ,,,,,,

Type RM Length L Ch R = 1 ,6863.5  ,149.9,173.4,201.8
BEGIN DESCRIPTION:
Steeple Way - 2
Formerly E135-00-00-04
END DESCRIPTION:
XS GIS Cut Line= 3
      3049576.15      13890730.7      3049439.36      13890370.3
      3048853.12      13889574.9
#Sta/Elev= 29
  4452.4  112.48 4493.21  111.57 4766.94  112.64 4832.23  110.82 4889.36  110.85
 4922.01  112.22 4954.65  112.51 4956.37  112.99 4982.16  101.37 4985.09  102.12
 4993.91  101.19 4997.17  101.02 5000.03  100.22 5005.25  100.51 5006.72  100.96
 5006.97  101.42  5007.7  101.37 5017.82  102.06 5038.96  110.32  5045.9  111.89
 5058.38   112.3 5068.91  112.27 5109.72  110.92  5134.2  111.36 5158.69  110.78
 5191.33  112.36 5485.14  112.99 5525.95  112.36 5573.45  112.88
#Mann= 5 ,-1 , 0
  4452.4     .08       0 4832.23     .05       0 4922.01     .04       0
 4956.37     .04       0  5045.9     .08       0
#XS Ineff= 2 , 0
   921.3 4964.12  112.23 5037.33   921.3  112.23
Permanent Ineff=
       F       F
Bank Sta=4956.37,5045.9
XS Rating Curve= 0
Skew Angle= 35.3
Exp/Cntr=.5,.3

Type RM Length L Ch R = 1 ,6690.1  ,841.5,831.2,821.3
BEGIN DESCRIPTION:
Steeple Way - 1
Fromerly Cross Section E135-00-00-X08
Located At: DS STEEPLE WAY
***Ineffective area in the right and left overbanks indicates ponding water***
END DESCRIPTION:
XS GIS Cut Line= 6
      3049570.89     13890565.42      3049466.34     13890347.96
      3049445.43     13890176.03      3049431.72     13890055.36
      3049395.25     13889816.86      3049181.97     13889595.23
#Sta/Elev= 29
  4534.6   113.9  4775.9   113.5  4785.9   113.4  4825.9   110.8  4835.9   110.4
  4851.5   110.4  4875.9   110.4  4885.9  111.22  4916.4  111.63  4953.2  112.07
  4980.3  103.37  4995.8  101.64  4996.2  100.53  4997.1   99.21  5000.5    99.5
  5003.4    99.6  5003.8  100.31  5015.5  103.63    5039  111.45  5064.4  111.06
  5112.4   111.6  5170.5   111.3  5200.5   110.5  5203.4  110.51  5230.5   110.6
  5270.5   113.4  5491.8   112.5  5581.8   113.7  5619.4   113.6
#Mann= 6 ,-1 , 0
  4534.6     .08       0  4851.5     .05       0  4916.4     .04       0
  4953.2     .04       0    5039     .05       0  5203.4     .08       0
#XS Ineff= 2 , 0
         4940.44  112.24 5111.62          112.47
Permanent Ineff=
       F       F
Bank Sta=4953.2,5039
XS Rating Curve= 0
Exp/Cntr=.3,.1

Type RM Length L Ch R = 1 ,5858.9  ,182.2,201.5,215.8
BEGIN DESCRIPTION:
Cross Section E135-00-00-X07
Located At: US JONES RD
***Ineffective area in the right and left overbanks indicates ponding water***
END DESCRIPTION:
XS GIS Cut Line= 4
      3050273.44     13890373.05      3050250.81     13889945.67
      3050133.99     13889598.49      3049968.16     13889331.77
#Sta/Elev= 30
  4440.1   113.2  4480.1   113.4  4490.1     113  4520.1   109.9  4550.1   109.2
  4730.1   110.1  4760.1   112.3  4790.1   110.3  4807.7   110.3  4870.7  110.63
  4906.9  108.75  4914.5  109.56  4920.8  110.24  4957.1  110.48  4982.5  101.84
  4996.4   99.34    4997   98.51  4999.4   98.38  5002.8   98.72  5003.6    99.4
  5004.2  100.63  5016.3  103.17  5041.5  111.31  5068.5  109.67  5086.4  111.39
    5159   110.1  5274.4   110.9  5364.4   110.3  5444.4   111.9  5548.5   113.1
#Mann= 6 ,-1 , 0
  4440.1     .08       0  4807.7     .05       0  4914.5     .04       0
  4957.1     .04       0  5041.5     .05       0    5159     .08       0
#XS Ineff= 2 , 0
         4821.31   111.4 5042.45           111.4
Permanent Ineff=
       F       F
Bank Sta=4957.1,5041.5
XS Rating Curve= 0
Exp/Cntr=.3,.1

Type RM Length L Ch R = 1 ,5657.4  ,100.3,98.4,98
BEGIN DESCRIPTION:
Jone Rd - 4
Interpolated channel, LIDAR overbanks
END DESCRIPTION:
XS GIS Cut Line= 4
      3050339.38      13890487.2      3050396.32     13889883.72
      3050403.54     13889646.76      3050395.66     13889054.79
#Sta/Elev= 30
  4282.1  112.76  4342.1  111.56  4382.1  113.14  4432.1  113.36  4462.1  110.95
  4492.1  109.76  4522.1  110.29  4552.1  112.29  4612.1  113.03  4732.1  112.86
  4762.1  110.21  4822.1  110.01  4842.1  110.61  4918.3   109.1  4958.3  109.99
 4958.51  108.48 4980.12  101.99 4994.97   99.58 4998.53   98.28 5002.49   98.71
 5006.36  101.58 5006.67  100.88 5013.88  102.65 5038.21   110.6  5048.3  111.59
  5165.4  109.87  5185.4     111  5275.4  112.18  5505.4  110.84  5717.4  111.87
#Mann= 6 ,-1 , 0
  4282.1     .08       0  4822.1     .05       0  4918.3     .04       0
  4958.3     .04       0 5038.21     .05       0  5165.4     .08       0
#XS Ineff= 2 , 0
       0  4842.1   111.4  5048.3       0  111.59
Permanent Ineff=
       F       F
Bank Sta=4958.3,5038.21
XS Rating Curve= 0
Exp/Cntr=.5,.3