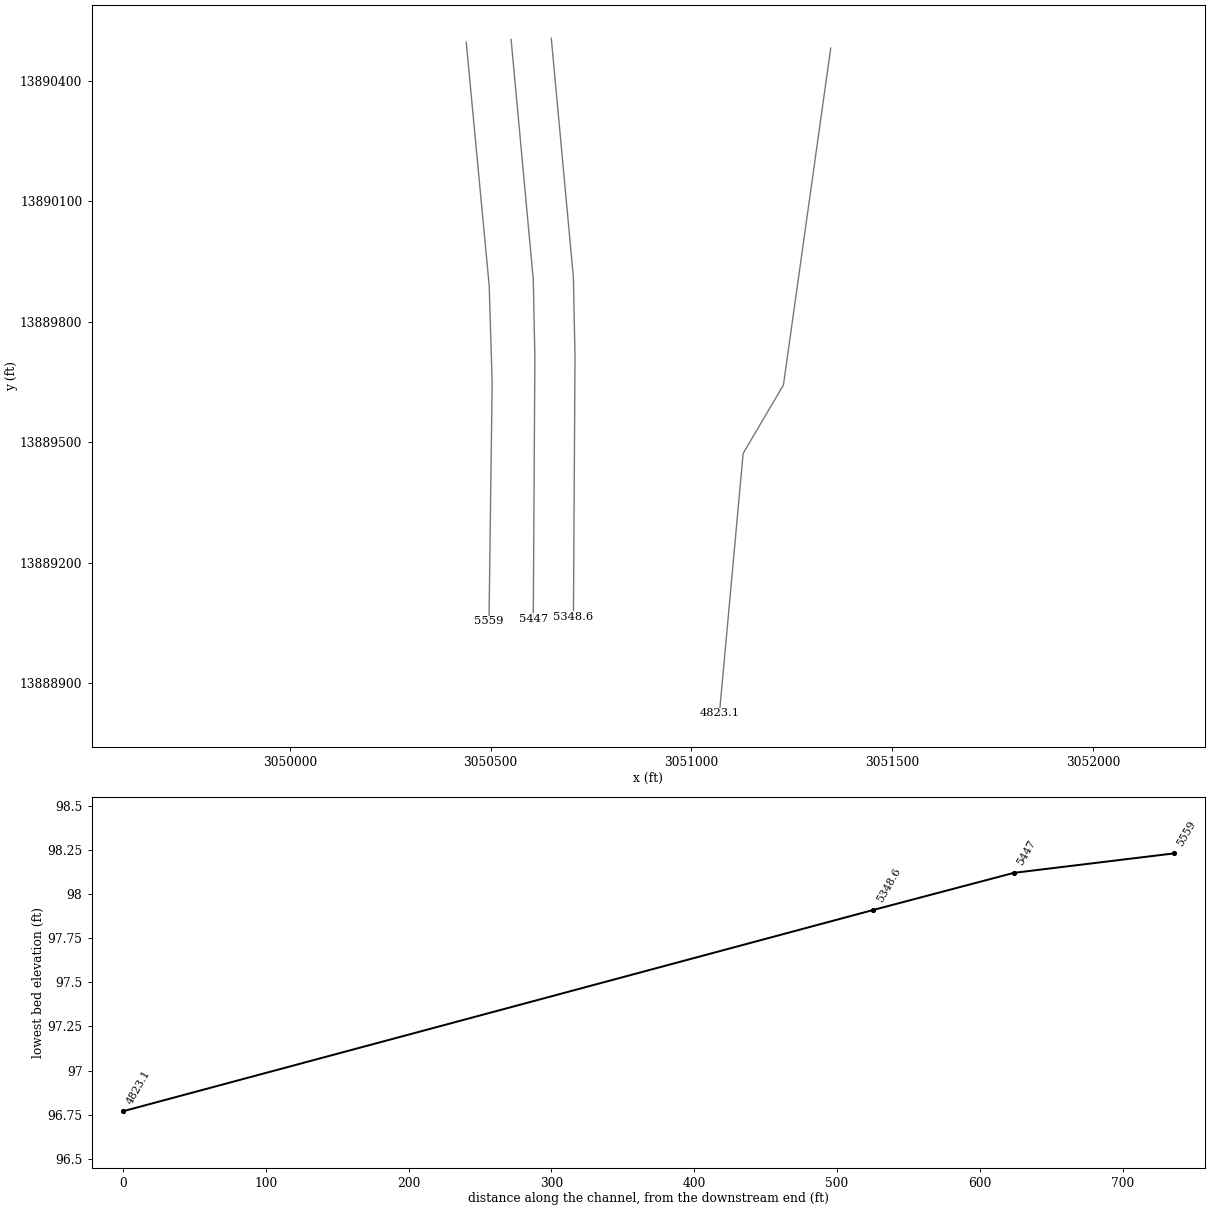
HEC-RAS study E135-00-00.prj: E135-00-00

--- E135-00-00.g01 (geometry) --- (continued)

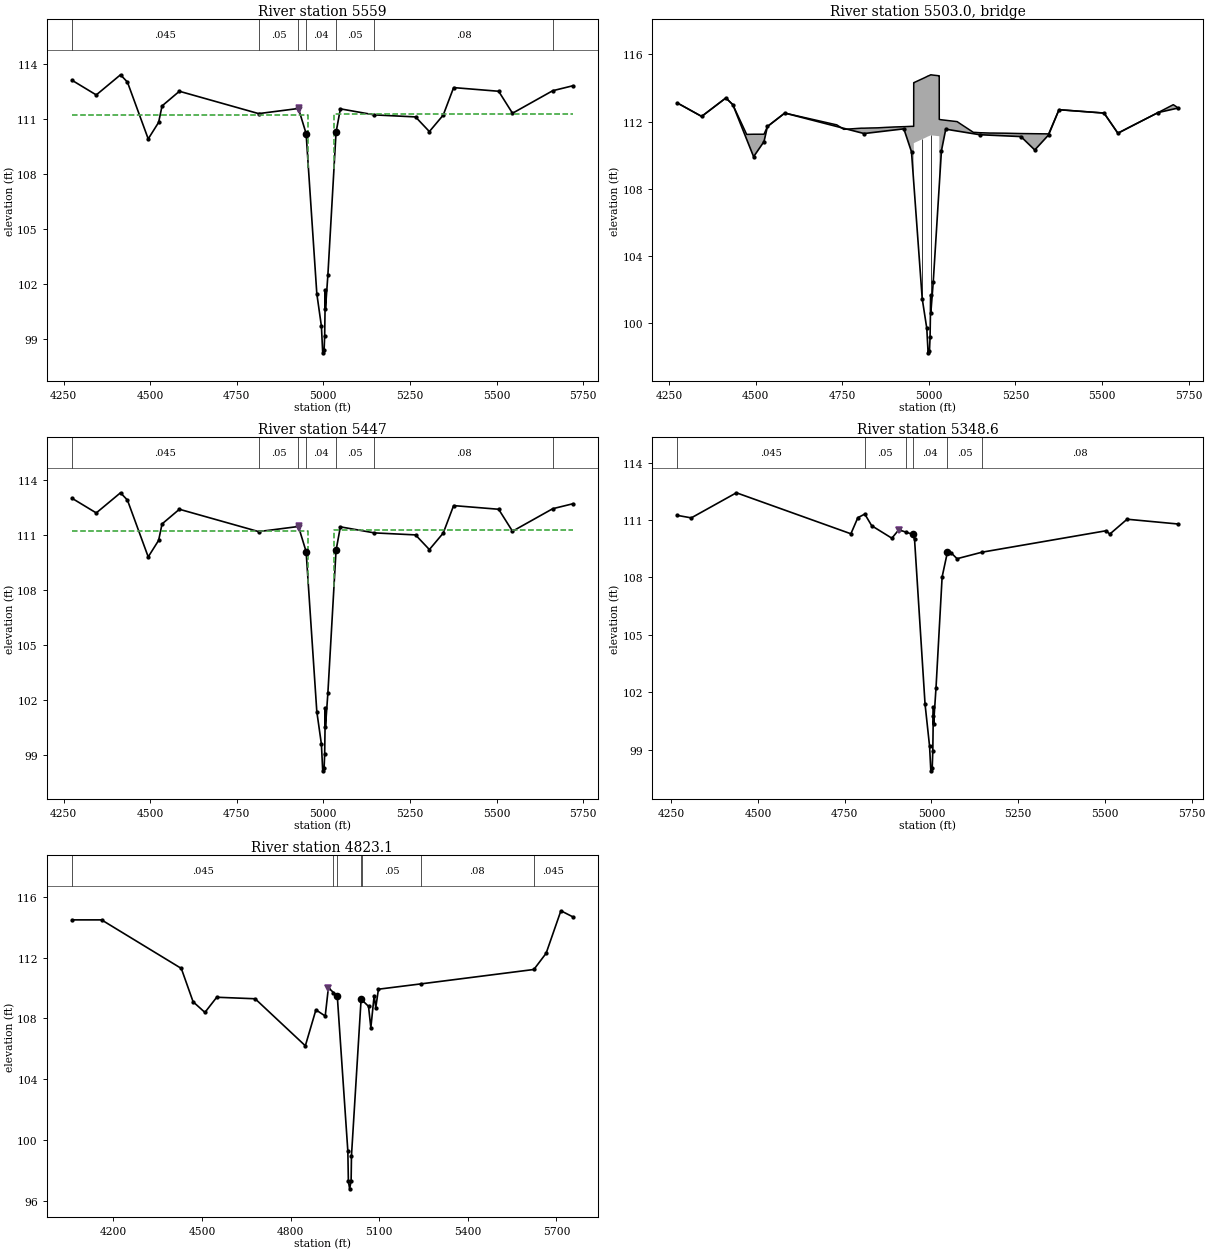
Type RM Length L Ch R = 1 ,5559    ,109.4,112,108.5
BEGIN DESCRIPTION:
Jone Rd - 3
Formerly E135-00-00-03
***The Levee option was used on this cross-section does not describe a certified levee system but because after reviewing the mapping it was determined that water under that elevation could not back up into the lower-lying areas in the left overbank.***
END DESCRIPTION:
XS GIS Cut Line= 4
      3050438.94     13890496.62      3050496.17     13889889.94
      3050503.56     13889647.62      3050495.65     13889053.46
#Sta/Elev= 30
  4274.3  113.11  4344.3  112.31  4414.3  113.41  4434.3  113.01  4494.3  109.91
  4524.3  110.81  4534.3  111.71  4584.3  112.51  4813.2  111.29  4928.1  111.57
  4950.2   110.2  4981.1  101.46  4994.4   99.68  4998.1   98.23  5002.1   98.36
  5003.8   99.16  5005.7  101.68    5006  100.61    5013  102.46  5036.6  110.26
  5049.1  111.55  5147.3  111.22  5266.1  111.11  5306.1  110.31  5346.1  111.21
  5376.1  112.71  5506.1  112.51  5546.1  111.31  5662.2  112.54  5720.3  112.81
#Mann= 7 ,-1 , 0
  4274.3    .045       0  4813.2     .05       0  4928.1     .04       0
  4950.2     .04       0  5036.6     .05       0  5147.3     .08       0
  5662.2     .08       0
Levee=-1,4929.3,111.58,0,,,,
#XS Ineff= 2 , 0
       0  4956.9  111.24  5030.6       0  111.27
Permanent Ineff=
       F       F
Bank Sta=4950.2,5036.6
XS Rating Curve= 0
Exp/Cntr=.5,.3

Type RM Length L Ch R = 3 ,5503.0  ,,,
BEGIN DESCRIPTION:
JONES ROAD
Structure ID: E135-00-00-03
***The Levee option was used on this cross-section does not describe a certified levee system but because after reviewing the mapping it was determined that water under that elevation could not back up into the lower-lying areas in the left overbank.***
END DESCRIPTION:
Bridge Culvert--1,0,-1,-1, 0
Deck Dist Width WeirC Skew NumUp NumDn MinLoCord MaxHiCord MaxSubmerge Is_Ogee
10,92,2.6,0, 66, 66, , , .95, 0, ,,,
  4274.3  4287.3  4344.3  4414.3  4434.3  4474.3  4494.3  4524.3  4534.3  4584.3
  4727.3  4734.3  4754.6  4805.3  4813.2  4828.5  4852.2  4878.4  4898.7  4928.1
  4929.3  4950.2 4956.49  4956.6 4956.71 4956.84  4956.9  4981.1  4988.4  4994.4
  4996.1  4998.1  4998.2  5002.1  5003.8  5005.1  5005.7  5005.8    5006    5013
 5030.16 5030.27 5030.38 5030.51  5030.6  5036.6  5049.1    5082  5091.3    5129
  5133.7  5147.3  5176.3  5183.9  5223.8  5266.1  5306.1  5346.1  5376.1  5506.1
  5546.1  5580.5  5662.2  5706.1  5714.2  5720.3
   113.1  112.96  112.31  113.41  113.01  111.24  111.25  111.25  111.71  112.51
  111.84  111.81  111.54  111.61  111.61  111.62  111.63  111.66  111.68   111.7
   111.7  111.72  111.72  114.32  114.32  114.32  114.32  114.55  114.62  114.68
   114.7  114.72  114.72  114.75  114.77  114.78  114.79  114.79  114.79  114.77
  114.73  114.73  112.13  112.13  112.13  112.11  112.08     112  111.87  111.36
  111.36  111.34  111.32  111.32  111.31  111.29  111.28  111.27  112.71  112.51
  111.31  111.68  112.54  113.01   112.9   112.8
                                                                                
                                                                                
                                                  110.72  110.95  111.02  111.08
   111.1  111.12  111.12  111.15  111.17  111.18  111.19  111.19  111.19  111.17
  111.13  111.13  111.13  111.13
                                                                                
                                                
  4274.3  4287.3  4344.3  4414.3  4434.3  4474.3  4494.3  4524.3  4534.3  4584.3
  4727.3  4734.3  4754.6  4805.3  4813.2  4828.5  4852.2  4878.4  4898.7  4928.1
  4929.3  4950.2 4956.49  4956.6 4956.71 4956.84  4956.9  4981.1  4988.4  4994.4
  4996.1  4998.1  4998.2  5002.1  5003.8  5005.1  5005.7  5005.8    5006    5013
 5030.16 5030.27 5030.38 5030.51  5030.6  5036.6  5049.1    5082  5091.3    5129
  5133.7  5147.3  5176.3  5183.9  5223.8  5266.1  5306.1  5346.1  5376.1  5506.1
  5546.1  5580.5  5662.2  5706.1  5714.2  5720.3
   113.1  112.96  112.31  113.41  113.01  111.24  111.25  111.25  111.71  112.51
  111.84  111.81  111.54  111.61  111.61  111.62  111.63  111.66  111.68   111.7
   111.7  111.72  111.72  114.32  114.32  114.32  114.32  114.55  114.62  114.68
   114.7  114.72  114.72  114.75  114.77  114.78  114.79  114.79  114.79  114.77
  114.73  114.73  112.13  112.13  112.13  112.11  112.08     112  111.87  111.36
  111.36  111.34  111.32  111.32  111.31  111.29  111.28  111.27  112.71  112.51
  111.31  111.68  112.54  113.01   112.9   112.8
                                                                                
                                                                                
                                                  110.72  110.95  111.02  111.08
   111.1  111.12  111.12  111.15  111.17  111.18  111.19  111.19  111.19  111.17
  111.13  111.13  111.13  111.13
                                                                                
                                                
Pier Skew, UpSta & Num, DnSta & Num=  ,4981.1, 2 ,4981.1, 2 , 0 , 0 , 0 ,,
     1.2     1.2
  100.35  111.96
     1.2     1.2
  100.27  111.88
Pier Skew, UpSta & Num, DnSta & Num=  ,5006, 2 ,5006, 2 , 0 , 0 , 0 ,,
     1.2     1.2
   99.76  112.19
     1.2     1.2
   99.68  112.11
BR Coef= 1 , 1 , 1 ,1.25, 0 ,,,.8,0,2,0,
WSPro=,,,, 1 ,,,, 0 ,,,, 0 ,,,,-1 ,-1 ,-1 , 0 , 0 , 0 , 0 , 0
BC Design=,, 0 ,, 0 ,,,,,,

Type RM Length L Ch R = 1 ,5447    ,100.2,98.4,98
BEGIN DESCRIPTION:
Jone Rd - 2
Formerly E135-00-00-03
***The Levee option was used on this cross-section does not describe a certified levee system but because after reviewing the mapping it was determined that water under that elevation could not back up into the lower-lying areas in the left overbank.***
END DESCRIPTION:
XS GIS Cut Line= 6
 3050550.717271413890503.2855592      3050551.29     13890497.09
      3050606.01     13889905.15      3050609.95     13889712.13
      3050606.01     13889066.11 3050605.972053613889059.8881408
#Sta/Elev= 30
  4274.3     113  4344.3   112.2  4414.3   113.3  4434.3   112.9  4494.3   109.8
  4524.3   110.7  4534.3   111.6  4584.3   112.4  4813.2  111.18  4928.1  111.46
  4950.2  110.09  4981.1  101.35  4994.4   99.57  4998.1   98.12  5002.1   98.25
  5003.8   99.05  5005.7  101.57    5006   100.5    5013  102.35  5036.6  110.15
  5049.1  111.44  5147.3  111.11  5266.1     111  5306.1   110.2  5346.1   111.1
  5376.1   112.6  5506.1   112.4  5546.1   111.2  5662.2  112.43  5720.3   112.7
#Mann= 7 ,-1 , 0
  4274.3    .045       0  4813.2     .05       0  4928.1     .04       0
  4950.2     .04       0  5036.6     .05       0  5147.3     .08       0
  5662.2     .08       0
Levee=-1,4929.29,111.47,0,,,,
#XS Ineff= 2 , 0
       0  4956.9  111.24  5030.6       0  111.27
Permanent Ineff=
       F       F
Bank Sta=4950.2,5036.6
XS Rating Curve= 0
Exp/Cntr=.5,.3

Type RM Length L Ch R = 1 ,5348.6  ,550,525.5,503.7
BEGIN DESCRIPTION:
Jone Rd -1
Interpolated channel, LIDAR overbanks
***The Levee option was used on this cross-section does not describe a certified levee system but because after reviewing the mapping it was determined that water under that elevation could not back up into the lower-lying areas in the left overbank.***
END DESCRIPTION:
XS GIS Cut Line= 4
      3050650.86      13890506.3      3050705.91     13889910.78
      3050709.95     13889712.85      3050706.01      13889065.5
#Sta/Elev= 30
    4268  111.24    4308  111.11    4438  112.42    4768  110.28    4788  111.12
    4808  111.31    4828   110.7  4886.1  110.05  4906.1  110.49  4926.1  110.37
  4946.1  110.25 4951.46  109.99 4981.74  101.39 4994.77   99.19  4998.4   97.91
  5002.4   98.08 5004.11   98.96 5005.41  100.78 5006.01  101.23 5006.31  100.34
 5013.32  102.24 5030.94  108.03  5046.1  109.31  5056.1   109.3    5074  108.98
    5146  109.32    5504  110.44    5514  110.26    5564  111.04  5711.4  110.79
#Mann= 6 ,-1 , 0
    4268    .045       0    4808     .05       0  4926.1     .04       0
  4946.1     .04       0  5046.1     .05       0    5146     .08       0
Levee=-1,4906.1,110.49,0,,,,
Bank Sta=4946.1,5046.1
XS Rating Curve= 0
Exp/Cntr=.3,.1

Type RM Length L Ch R = 1 ,4823.1  ,841,849.1,856.1
BEGIN DESCRIPTION:
Cross Section E135-00-00-X06
Located At: DS JONES RD
***The Levee option was used on this cross-section does not describe a certified levee system but because after reviewing the mapping it was determined that water under that elevation could not back up into the lower-lying areas in the left overbank.***
END DESCRIPTION:
XS GIS Cut Line= 4
      3051347.04     13890481.95      3051229.25     13889642.64
      3051128.84     13889472.23      3051069.75     13888824.52
#Sta/Elev= 30
    4060   114.5    4160   114.5    4430   111.3    4470   109.1    4510   108.4
    4550   109.4    4680   109.3    4850   106.2  4885.8  108.57  4917.3  108.16
  4928.1  110.03  4945.2  109.71  4958.2  109.47  4993.9   99.26  4995.7   97.27
    5000   96.77    5005   97.29  5006.2   98.95  5038.8  109.27  5042.7   109.2
  5063.9   108.8  5071.8  107.39    5083  109.51  5088.5  108.72  5097.5  109.93
    5241  110.28  5623.8  111.23  5665.3   112.3  5715.3   115.1  5755.7   114.7
#Mann= 7 ,-1 , 0
    4060    .045       0  4945.2     .04       0  4958.2     .04       0
  5038.8     .04       0  5042.7     .05       0    5241     .08       0
  5623.8    .045       0
Levee=-1,4928.1,110.03,0,,,,
Bank Sta=4958.2,5038.8
XS Rating Curve= 0
Exp/Cntr=.3,.1