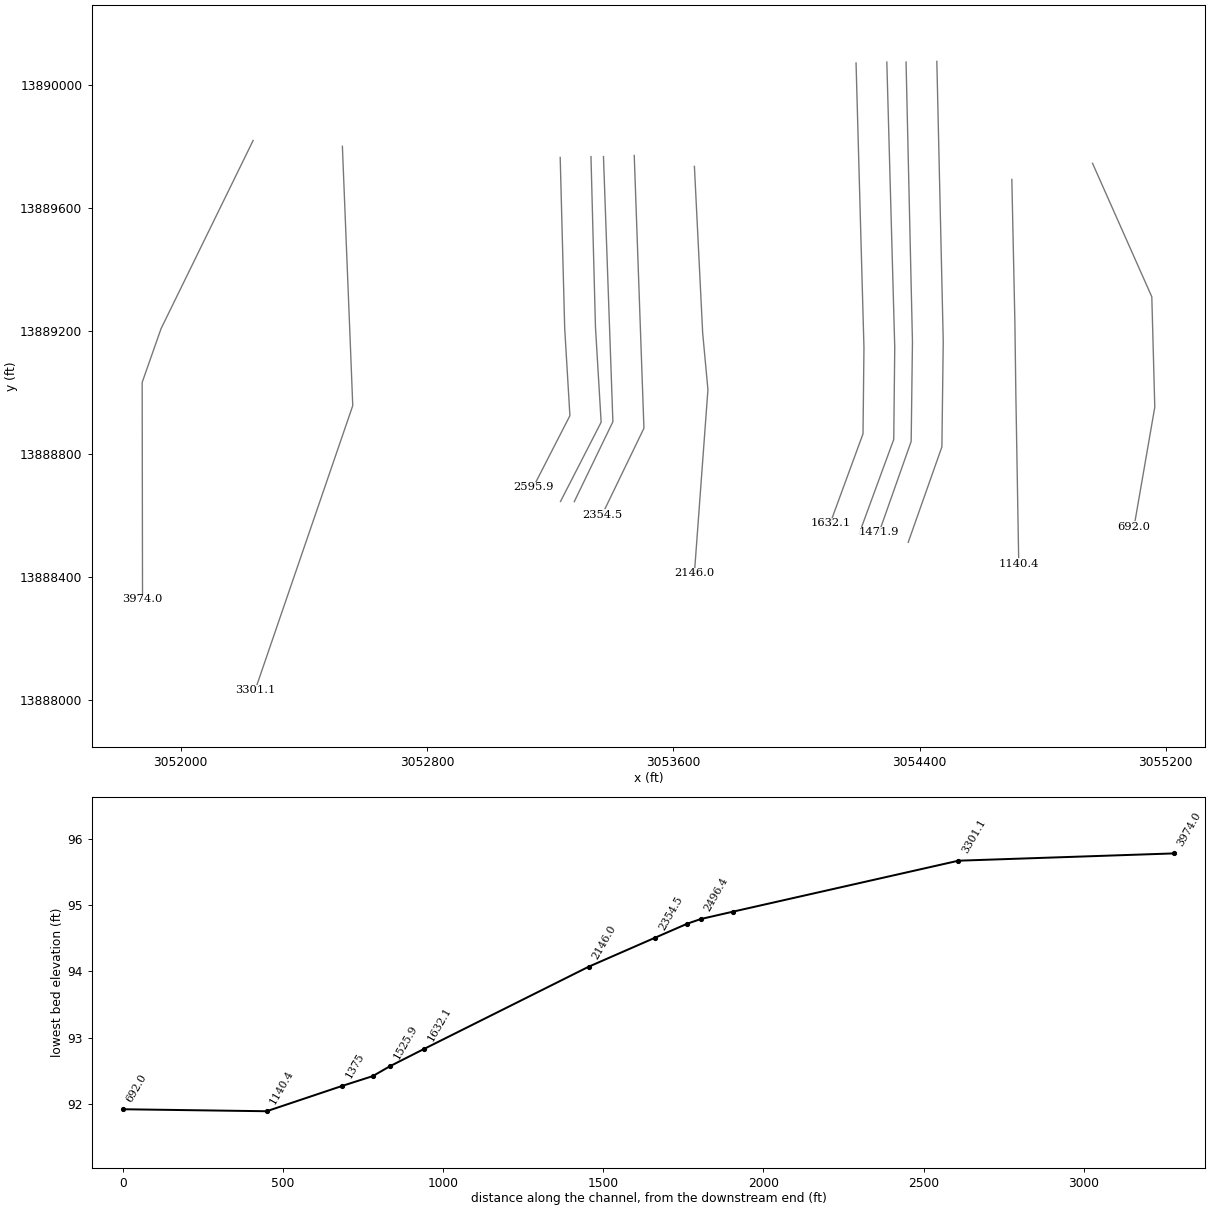
HEC-RAS study E135-00-00.prj: E135-00-00

--- E135-00-00.g01 (geometry) --- (continued)

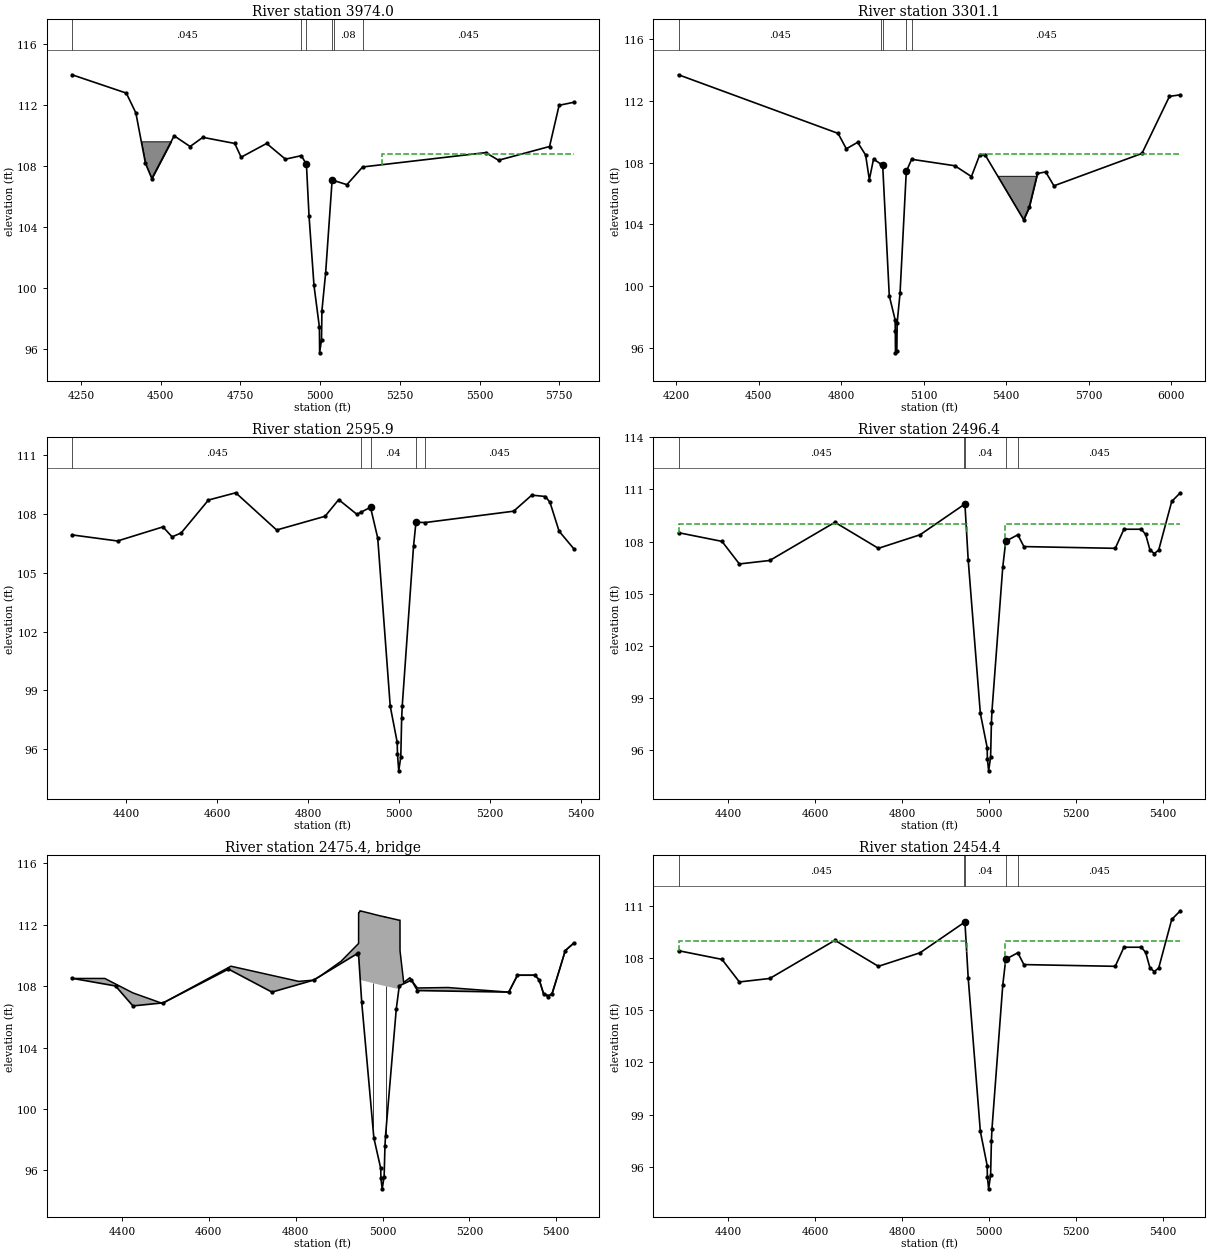
Type RM Length L Ch R = 1 ,3974.0  ,652.2,672.9,685.4
BEGIN DESCRIPTION:
Cross Section E135-00-00-X05
***Blocked-out area reflects a small drainage channel .***
***Ineffective area in the right overbank indicates ponding water***
END DESCRIPTION:
XS GIS Cut Line= 4
      3052235.62     13889820.24      3051936.59     13889207.73
      3051875.27     13889032.89      3051876.41     13888326.66
#Sta/Elev= 30
  4222.5     114  4392.5   112.8  4422.5   111.5  4452.5   108.2  4472.5   107.2
  4542.5     110  4592.5   109.3  4632.5   109.9  4732.5   109.5  4752.5   108.6
  4832.5   109.5  4891.4  108.47  4941.2   108.7  4957.2  108.14  4965.3  104.77
  4980.9   100.2  4997.9   97.46  4998.6   95.78  5004.5   96.65  5005.8   98.55
  5017.4  101.01  5037.7  107.08  5043.3  107.07  5084.1   106.8  5133.4  107.96
  5519.4   108.9  5559.4   108.4  5719.4   109.3  5749.4     112  5795.6   112.2
#Mann= 6 ,-1 , 0
  4222.5    .045       0  4941.2     .04       0  4957.2     .04       0
  5037.7     .04       0  5043.3     .08       0  5133.4    .045       0
#XS Ineff= 2 , 0
                         5194.93          108.78
Permanent Ineff=
       F       F
#Block Obstruct= 1 ,-1
 4423.58 4535.37  109.64
Bank Sta=4957.2,5037.7
XS Rating Curve= 0
Exp/Cntr=.3,.1

Type RM Length L Ch R = 1 ,3301.1  ,700.1,705.2,701.8
BEGIN DESCRIPTION:
Cross Section E135-00-00-X04
Located At: 2ND US RIO GRANDE
***Blocked-out area reflects a small drainage channel through the golf course.***
***The ineffective area in the right overbank indicates flow that leave E135-00-00 and goes down an unknown small drainage channel through the golf course.***
END DESCRIPTION:
XS GIS Cut Line= 4
      3052525.52     13889801.33      3052552.53     13889127.09
       3052559.2      13888957.2      3052241.93     13888030.47
#Sta/Elev= 30
  4208.9   113.7  4788.9   109.9  4818.9   108.9    4860  109.32    4889   108.5
  4902.6   106.9  4917.8  108.23  4944.6  107.91  4951.1  107.83  4975.1   99.37
  4996.3   97.81    4997   97.07  4997.6   95.67  5002.6   95.82  5003.6   97.59
  5014.2   99.53  5036.9  107.43  5056.3  108.22  5213.7   107.8  5273.7   107.1
  5303.7   108.5  5323.7   108.5  5463.7   104.3  5483.7   105.1  5513.7   107.3
  5543.7   107.4  5573.7   106.5  5893.7   108.6  5993.7   112.3  6033.2   112.4
#Mann= 5 ,-1 , 0
  4208.9    .045       0  4944.6     .04       0  4951.1     .04       0
  5036.9     .04       0  5056.3    .045       0
#XS Ineff= 2 , 0
                         5303.49          108.59
Permanent Ineff=
       F       F
#Block Obstruct= 1 ,-1
 5318.78  5526.2  107.15
Bank Sta=4951.1,5036.9
XS Rating Curve= 0
Exp/Cntr=.3,.1

Type RM Length L Ch R = 1 ,2595.9  ,99,99.5,100
BEGIN DESCRIPTION:
Golf Cart Bridge - 4
Interpolated channel, LIDAR overbanks
END DESCRIPTION:
XS GIS Cut Line= 4
      3053232.95      13889765.1      3053247.58     13889208.79
       3053264.5     13888924.52      3053144.97     13888690.84
#Sta/Elev= 30
  4280.4  106.94  4380.4  106.63  4480.4  107.35  4500.4  106.84  4520.4  107.04
  4580.4  108.72  4640.4  109.09  4730.4  107.19  4836.9  107.89  4866.9  108.74
  4906.9  107.99  4916.9  108.11  4936.9  108.35 4952.77  106.78 4980.25    98.2
 4995.66   96.35 4996.16   95.78    4999    94.9  5003.5   95.61  5005.4   97.58
  5006.7   98.22 5031.49  106.35 5036.88  107.59  5056.9  107.57  5251.7  108.15
  5291.7  108.97  5321.7   108.9  5331.7   108.6  5351.7  107.13  5384.2  106.23
#Mann= 5 ,-1 , 0
  4280.4    .045       0  4916.9     .04       0  4936.9     .04       0
 5036.88     .04       0  5056.9    .045       0
Bank Sta=4936.9,5036.88
XS Rating Curve= 0
Exp/Cntr=.5,.3

Type RM Length L Ch R = 1 ,2496.4  ,42.9,42,40.8
BEGIN DESCRIPTION:
Golf Cart Bridge - 3
Formerly E135-00-00-02
END DESCRIPTION:
XS GIS Cut Line= 4
      3053332.91     13889767.75       3053347.5     13889213.07
      3053365.94     13888903.25        3053234.      13888645.3
#Sta/Elev= 30
  4285.4  108.51  4385.4  108.01  4425.4  106.71  4495.4  106.91  4645.4  109.11
  4745.4  107.61  4841.3  108.39  4941.4  110.11  4944.6  110.16  4952.1  106.95
  4980.1    98.1  4995.8   96.13  4996.3   95.48  4999.2   94.79  5003.7   95.58
  5005.6   97.57  5006.9   98.26  5031.7  106.53  5038.6  108.02  5066.4  108.39
  5080.3  107.71  5290.6  107.61  5310.6  108.71  5350.6  108.71  5360.6  108.41
  5370.6  107.51  5380.6  107.31  5390.6  107.51  5420.6  110.31  5440.4  110.81
#Mann= 5 ,-1 , 0
  4285.4    .045       0  4941.4     .04       0  4944.6     .04       0
  5038.6     .04       0  5066.4    .045       0
#XS Ineff= 2 , 0
       0  4948.6     109  5037.1       0     109
Permanent Ineff=
       F       F
Bank Sta=4944.6,5038.6
XS Rating Curve= 0
Exp/Cntr=.5,.3

Type RM Length L Ch R = 3 ,2475.4  ,,,
BEGIN DESCRIPTION:
GOLF CART BRIDGE
Structure ID: E135-00-00-02
END DESCRIPTION:
Bridge Culvert--1,0,-1,-1, 0
Deck Dist Width WeirC Skew NumUp NumDn MinLoCord MaxHiCord MaxSubmerge Is_Ogee
10,22,2.6,0, 63, 63, , , .95, 0, ,,,
  4285.4  4360.8  4385.4  4425.4  4490.8  4495.4  4645.4  4650.8  4745.4  4807.1
  4840.8  4841.3  4856.8  4904.6  4941.4  4944.6 4944.89    4945 4945.11  4947.8
  4947.9 4948.62 4948.74 4948.81  4952.1  4977.8  4980.1  4995.8  4996.3  4998.7
  4999.2  5003.7  5005.6  5005.7  5006.9  5031.7 5037.12  5037.2  5037.3  5038.6
 5040.09  5040.2 5040.31  5048.7  5063.1  5066.2  5066.4  5080.3  5150.6  5186.8
  5290.6  5310.6  5350.6  5360.6  5370.6  5380.6  5386.8  5390.6  5406.8  5416.8
  5420.6  5429.2  5440.4
   108.5   108.5  108.14  107.56   106.9  106.91  109.21   109.3   108.7  108.31
  108.39  108.39  108.66  109.62  110.68  110.77  110.78  112.78  112.78  112.86
  112.91   112.9   112.9   112.9  112.88   112.7  112.68  112.57  112.57  112.55
  112.55  112.52  112.51   112.5   112.5  112.34   112.3   112.3   112.3   112.3
   112.3   112.3   110.3  108.24  108.55   108.4  108.39  107.88  107.91  107.83
  107.61  108.71  108.71  108.41  107.51  107.41  107.43  107.57  109.02  109.96
  110.31  110.53   110.8
                                                                                
                                                                   108.3   108.3
  108.41   108.4   108.4   108.4  108.38   108.2  108.18  108.07  108.07  108.05
  108.05  108.02  108.01     108     108  107.84   107.8
                                                                                
                                                                                
                        
  4285.4  4360.8  4385.4  4425.4  4490.8  4495.4  4645.4  4650.8  4745.4  4807.1
  4840.8  4841.3  4856.8  4904.6  4941.4  4944.6 4944.89    4945 4945.11  4947.8
  4947.9 4948.62 4948.74 4948.81  4952.1  4977.8  4980.1  4995.8  4996.3  4998.7
  4999.2  5003.7  5005.6  5005.7  5006.9  5031.7 5037.12  5037.2  5037.3  5038.6
 5040.09  5040.2 5040.31  5048.7  5063.1  5066.2  5066.4  5080.3  5150.6  5186.8
  5290.6  5310.6  5350.6  5360.6  5370.6  5380.6  5386.8  5390.6  5406.8  5416.8
  5420.6  5429.2  5440.4
   108.5   108.5  108.14  107.56   106.9  106.91  109.21   109.3   108.7  108.31
  108.39  108.39  108.66  109.62  110.68  110.77  110.78  112.78  112.78  112.86
  112.91   112.9   112.9   112.9  112.88   112.7  112.68  112.57  112.57  112.55
  112.55  112.52  112.51   112.5   112.5  112.34   112.3   112.3   112.3   112.3
   112.3   112.3   110.3  108.24  108.55   108.4  108.39  107.88  107.91  107.83
  107.61  108.71  108.71  108.41  107.51  107.41  107.43  107.57  109.02  109.96
  110.31  110.53   110.8
                                                                                
                                                                   108.3   108.3
  108.41   108.4   108.4   108.4  108.38   108.2  108.18  108.07  108.07  108.05
  108.05  108.02  108.01     108     108  107.84   107.8
                                                                                
                                                                                
                        
Pier Skew, UpSta & Num, DnSta & Num=  ,4977.8, 2 ,4977.8, 2 , 0 , 0 , 0 ,,
      .1      .1
   97.77   109.2
      .1      .1
   97.73  109.16
Pier Skew, UpSta & Num, DnSta & Num=  ,5006.9, 2 ,5006.9, 2 , 0 , 0 , 0 ,,
      .1      .1
   97.22     109
      .1      .1
   97.18  108.96
Abutment Skew #Up #Dn= , 2 , 2
  5005.7 5037.29
   97.61   107.8
  5005.7 5037.29
   97.57  107.76
BR Coef= 1 , 1 , 1 ,1.25, 0 ,,,.8,0,2,0,
WSPro=,,,, 1 ,,,, 0 ,,,, 0 ,,,,-1 ,-1 ,-1 , 0 , 0 , 0 , 0 , 0
BC Design=,, 0 ,, 0 ,,,,,,

Type RM Length L Ch R = 1 ,2454.4  ,100,99.9,99.5
BEGIN DESCRIPTION:
Golf Cart Bridge - 2
Formerly E135-00-00-02
END DESCRIPTION:
XS GIS Cut Line= 3
      3053373.52     13889767.86      3053404.12     13888904.84
      3053278.65     13888644.71
#Sta/Elev= 30
  4285.4  108.44  4385.4  107.94  4425.4  106.64  4495.4  106.84  4645.4  109.04
  4745.4  107.54  4841.3  108.32  4941.4  110.04  4944.6  110.09  4952.1  106.88
  4980.1   98.03  4995.8   96.06  4996.3   95.41  4999.2   94.72  5003.7   95.51
  5005.6    97.5  5006.9   98.19  5031.7  106.46  5038.6  107.95  5066.4  108.32
  5080.3  107.64  5290.6  107.54  5310.6  108.64  5350.6  108.64  5360.6  108.34
  5370.6  107.44  5380.6  107.24  5390.6  107.44  5420.6  110.24  5440.4  110.74
#Mann= 5 ,-1 , 0
  4285.4    .045       0  4941.4     .04       0  4944.6     .04       0
  5038.6     .04       0  5066.4    .045       0
#XS Ineff= 2 , 0
       0  4948.6     109  5037.1       0     109
Permanent Ineff=
       F       F
Bank Sta=4944.6,5038.6
XS Rating Curve= 0
Exp/Cntr=.5,.3

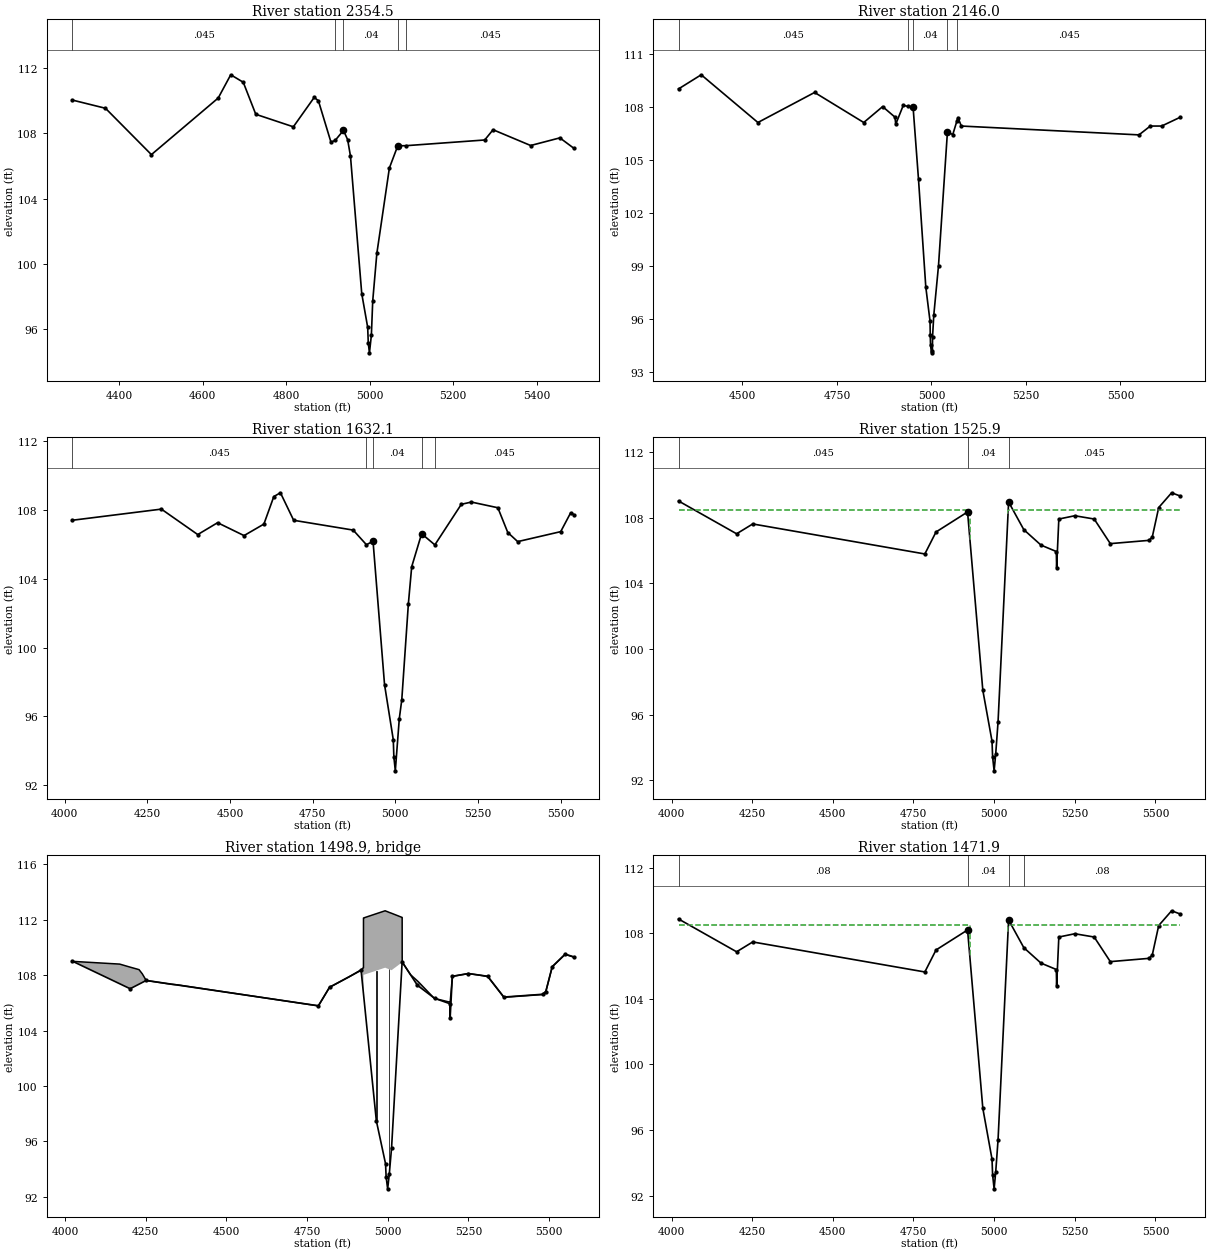
Type RM Length L Ch R = 1 ,2354.5  ,206.4,208.5,211
BEGIN DESCRIPTION:
Golf Cart Bridge - 1
Interpolated channel, LIDAR overbanks
END DESCRIPTION:
XS GIS Cut Line= 3
      3053473.45      13889771.4      3053504.93     13888883.67
      3053368.72     13888601.26
#Sta/Elev= 30
  4287.3  110.06  4367.3  109.55  4477.3   106.7  4637.3  110.18  4667.3  111.61
  4697.3  111.15  4727.3  109.18  4817.3  108.41  4867.3  110.22  4877.3  110.01
  4907.3  107.47  4917.3  107.57  4937.3  108.19  4947.3  107.62 4954.07  106.61
 4981.09   98.15  4995.3   96.08 4996.73   95.11 4999.52   94.51 5004.12   95.59
  5007.4   97.71 5017.22  100.62  5047.3  105.88  5067.3  107.24  5087.3  107.25
  5275.6   107.6  5295.6  108.23  5385.6  107.26  5455.6  107.73  5489.1  107.09
#Mann= 5 ,-1 , 0
  4287.3    .045       0  4917.3     .04       0  4937.3     .04       0
  5067.3     .04       0  5087.3    .045       0
Bank Sta=4937.3,5067.3
XS Rating Curve= 0
Exp/Cntr=.3,.1

Type RM Length L Ch R = 1 ,2146.0  ,517,513.9,508
BEGIN DESCRIPTION:
Cross Section E135-00-00-X03
Located At: US RIO GRANDE
END DESCRIPTION:
XS GIS Cut Line= 4
      3053668.86     13889735.93      3053695.71     13889193.76
      3053712.78     13889009.22      3053668.86     13888411.35
#Sta/Elev= 30
  4330.9     109  4390.9   109.8  4540.9   107.1  4690.9   108.8  4820.9   107.1
  4870.9     108  4903.7   107.4  4905.5     107  4925.5  108.07  4938.5  108.01
  4951.5  107.96  4965.8  103.88  4985.1   97.79  4996.3   95.86  4996.9   95.09
  4997.6    94.5  5000.2   94.07  5002.6   94.19    5003   94.99  5006.2    96.2
  5018.7      99  5042.3  106.56  5056.5  106.42    5067  107.16  5070.1  107.38
  5079.1   106.9  5549.1   106.4  5579.1   106.9  5609.1   106.9  5658.5   107.4
#Mann= 5 ,-1 , 0
  4330.9    .045       0  4938.5     .04       0  4951.5     .04       0
  5042.3     .04       0    5067    .045       0
Bank Sta=4951.5,5042.3
XS Rating Curve= 0
Exp/Cntr=.3,.1

Type RM Length L Ch R = 1 ,1632.1  ,100.2,106.2,100.1
BEGIN DESCRIPTION:
Rio Grande - 4
Interpolated channel, LIDAR overbanks
END DESCRIPTION:
XS GIS Cut Line= 4
      3054193.85      13890072.6      3054219.53     13889146.06
      3054216.47     13888865.58      3054110.04     13888574.67
#Sta/Elev= 30
  4022.6   107.4  4292.6  108.05  4402.6  106.57  4462.6  107.26  4542.6  106.51
  4602.6  107.18  4632.6  108.78  4652.6     109  4692.6   107.4  4872.6  106.83
  4912.6  105.98  4932.6  106.18  4967.4   97.84 4993.82   94.64 4995.58   93.64
 4999.95   92.83 5012.02   95.87  5019.5   96.96  5039.5  102.56  5049.5   104.7
  5079.5  106.62  5119.5  105.97  5199.5  108.33    5230  108.46    5310  108.13
    5340  106.69    5370  106.16    5500  106.74    5530  107.83  5539.8  107.73
#Mann= 5 ,-1 , 0
  4022.6    .045       0  4912.6     .04       0  4932.6     .04       0
  5079.5     .04       0  5119.5    .045       0
Bank Sta=4932.6,5079.5
XS Rating Curve= 0
Exp/Cntr=.5,.3

Type RM Length L Ch R = 1 ,1525.9  ,57.4,54,53.5
BEGIN DESCRIPTION:
Rio Grande - 3
Formerly E135-00-00-01
END DESCRIPTION:
XS GIS Cut Line= 4
      3054293.81     13890075.39      3054319.54      13889146.9
      3054316.28     13888847.33      3054203.95     13888540.32
#Sta/Elev= 26
  4021.7  109.02  4201.7  107.02  4251.7  107.62  4785.2  105.79  4819.8  107.13
  4917.6  108.35  4964.9   97.48  4993.4   94.38  4995.2   93.43  4999.9   92.57
  5004.9   93.61  5012.1   95.55  5044.8  108.96    5092  107.27  5145.2  106.33
  5192.7  105.94  5193.7  104.94  5200.5  107.92  5250.1  108.12  5310.1  107.92
  5360.1  106.42  5480.1  106.62  5490.1  106.82  5510.1  108.62  5550.1  109.52
  5577.1  109.32
#Mann= 3 ,-1 , 0
  4021.7    .045       0  4917.6     .04       0  5044.8    .045       0
#XS Ineff= 2 , 0
       0    4925   108.5    5043       0   108.5
Permanent Ineff=
       F       F
Bank Sta=4917.6,5044.8
XS Rating Curve= 0
Exp/Cntr=.5,.3

Type RM Length L Ch R = 3 ,1498.9  ,,,
BEGIN DESCRIPTION:
RIO GRANDE STREET
Structure ID: E135-00-00-01
END DESCRIPTION:
Bridge Culvert--1,0,-1,-1, 0
Deck Dist Width WeirC Skew NumUp NumDn MinLoCord MaxHiCord MaxSubmerge Is_Ogee
10,34,2.6,0, 56, 56, , , .95, 0, ,,,
  4021.7  4169.3  4201.7  4229.3  4239.3  4251.7  4259.3  4269.3  4329.3  4349.3
  4785.2  4819.8  4829.3  4833.6  4880.6  4917.6  4924.7 4924.81 4924.89    4925
  4925.1 4925.18  4964.9  4992.1  4993.4  4995.2  4999.9  5004.9  5012.1 5044.72
  5044.8  5044.9 5045.01  5071.1  5075.3    5092  5094.8 5143.89    5144  5144.1
  5145.2  5145.4  5192.7  5193.7  5200.5  5250.1  5275.4  5295.4  5296.7  5310.1
  5360.1  5480.1  5490.1  5510.1  5550.1  5577.1
     109   108.8  108.58   108.4   108.1  107.61  107.58  107.55  107.34   107.3
  105.78  107.12  107.24  107.29  107.88  108.39  108.53  108.53  108.53  112.13
  112.13  112.13  112.44  112.65  112.64  112.62  112.58  112.53  112.47  112.17
  112.17  112.17  108.94  108.03  107.94  107.59  107.53  106.34  106.34  106.34
  106.32  106.32  106.05  106.05  107.91  108.11  108.03  107.96  107.95   107.9
   106.4   106.6   106.8   108.6   109.5   109.3
                                                                                
                                                                                
          108.02  108.33  108.54  108.53  108.51  108.47  108.42  108.36  108.06
                                                                                
                                                                                
                                                
  4021.7  4169.3  4201.7  4229.3  4239.3  4251.7  4259.3  4269.3  4329.3  4349.3
  4785.2  4819.8  4829.3  4833.6  4880.6  4917.6  4924.7 4924.81 4924.89    4925
  4925.1 4925.18  4964.9  4992.1  4993.4  4995.2  4999.9  5004.9  5012.1 5044.72
  5044.8  5044.9 5045.01  5071.1  5075.3    5092  5094.8 5143.89    5144  5144.1
  5145.2  5145.4  5192.7  5193.7  5200.5  5250.1  5275.4  5295.4  5296.7  5310.1
  5360.1  5480.1  5490.1  5510.1  5550.1  5577.1
     109   108.8  108.58   108.4   108.1  107.61  107.58  107.55  107.34   107.3
  105.78  107.12  107.24  107.29  107.88  108.39  108.53  108.53  108.53  112.13
  112.13  112.13  112.44  112.65  112.64  112.62  112.58  112.53  112.47  112.17
  112.17  112.17  108.94  108.03  107.94  107.59  107.53  106.34  106.34  106.34
  106.32  106.32  106.05  106.05  107.91  108.11  108.03  107.96  107.95   107.9
   106.4   106.6   106.8   108.6   109.5   109.3
                                                                                
                                                                                
          108.02  108.33  108.54  108.53  108.51  108.47  108.42  108.36  108.06
                                                                                
                                                                                
                                                
Pier Skew, UpSta & Num, DnSta & Num=  ,4964.9, 2 ,4964.9, 2 , 0 , 0 , 0 ,,
     1.3     1.3
   96.39  109.34
     1.3     1.3
   96.28  109.23
Pier Skew, UpSta & Num, DnSta & Num=  ,5004.6, 2 ,5004.6, 2 , 0 , 0 , 0 ,,
     1.3     1.3
   92.39  109.43
     1.3     1.3
   92.28  109.32
BR Coef= 1 , 1 , 1 ,1.25, 0 ,,,.8,0,2,0,
WSPro=,,,, 1 ,,,, 0 ,,,, 0 ,,,,-1 ,-1 ,-1 , 0 , 0 , 0 , 0 , 0
BC Design=,, 0 ,, 0 ,,,,,,

Type RM Length L Ch R = 1 ,1471.9  ,100.2,96.9,96.5
BEGIN DESCRIPTION:
Rio Grande - 2
Formerly E135-00-00-01
END DESCRIPTION:
XS GIS Cut Line= 4
      3054356.25     13890075.55      3054377.04     13889165.08
      3054372.88      13888840.8      3054268.94     13888545.63
#Sta/Elev= 26
  4021.7  108.87  4201.7  106.87  4251.7  107.47  4785.2  105.64  4819.8  106.98
  4917.6   108.2  4964.9   97.33  4993.4   94.23  4995.2   93.28  4999.9   92.42
  5004.9   93.46  5012.1    95.4  5044.8  108.81    5092  107.12  5145.2  106.18
  5192.7  105.79  5193.7  104.79  5200.5  107.77  5250.1  107.97  5310.1  107.77
  5360.1  106.27  5480.1  106.47  5490.1  106.67  5510.1  108.47  5550.1  109.37
  5577.1  109.17
#Mann= 4 ,-1 , 0
  4021.7     .08       0  4917.6     .04       0  5044.8     .04       0
    5092     .08       0
#XS Ineff= 2 , 0
       0    4925   108.5    5043       0   108.5
Permanent Ineff=
       F       F
Bank Sta=4917.6,5044.8
XS Rating Curve= 0
Exp/Cntr=.5,.3

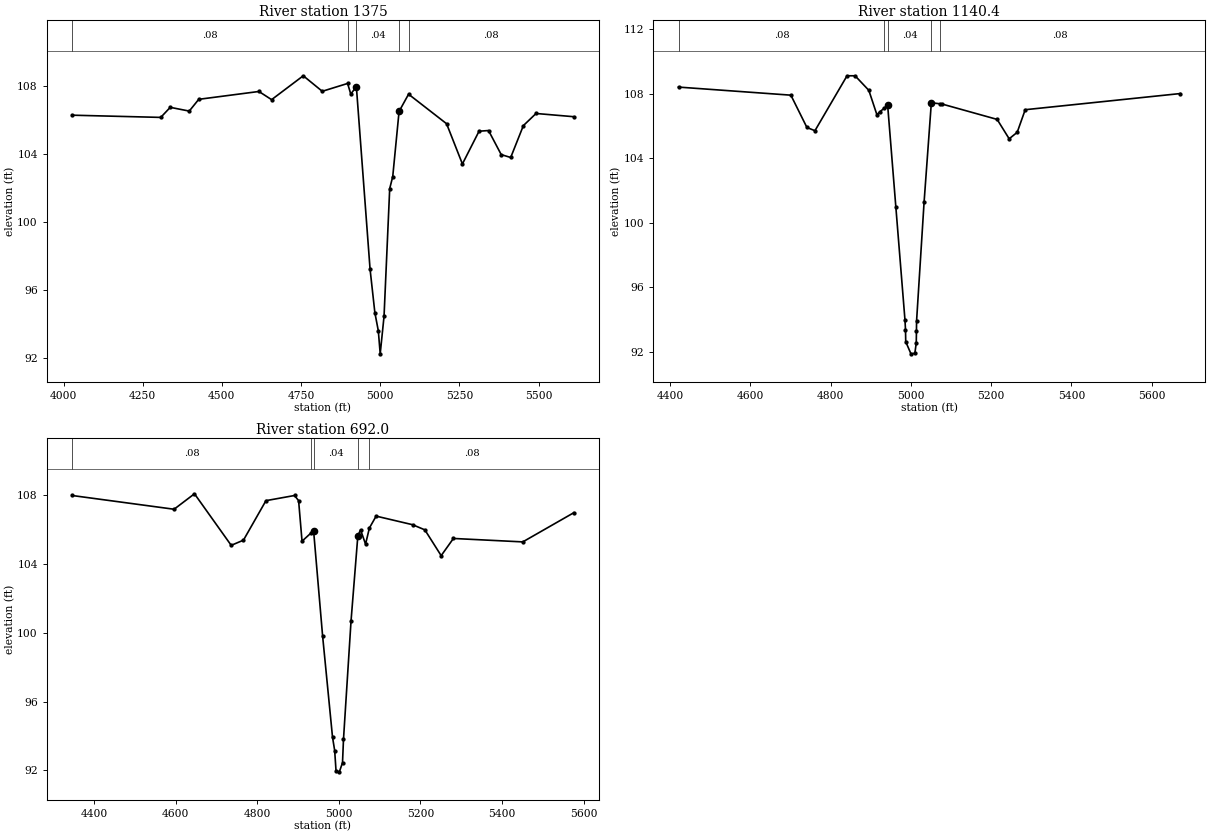
Type RM Length L Ch R = 1 ,1375    ,233.9,234.6,236.3
BEGIN DESCRIPTION:
Rio Grande - 1
Interpolated channel, LIDAR overbanks
END DESCRIPTION:
XS GIS Cut Line= 4
      3054456.22      13890077.8      3054477.05     13889165.58
      3054472.66     13888823.09      3054363.27     13888512.41
#Sta/Elev= 30
    4027  106.26    4307  106.13    4337  106.72    4397   106.5    4427  107.19
    4617  107.65    4657  107.17    4757  108.57    4817  107.66    4897  108.12
    4907   107.5  4924.7  107.93 4967.94   97.23  4983.1   94.68 4993.99   93.62
 4999.93   92.27 5012.04   94.47 5029.94  101.96  5039.5  102.66  5059.5  106.48
  5089.5  107.49  5209.5  105.76  5259.5   103.4    5312  105.32    5342  105.36
    5382  103.95    5412  103.78    5452  105.65    5492  106.36  5611.4  106.17
#Mann= 5 ,-1 , 0
    4027     .08       0    4897     .04       0  4924.7     .04       0
  5059.5     .04       0  5089.5     .08       0
Bank Sta=4924.7,5059.5
XS Rating Curve= 0
Exp/Cntr=.3,.1

Type RM Length L Ch R = 1 ,1140.4  ,447.8,448.4,449
BEGIN DESCRIPTION:
Cross Section E135-00-00-X02
Located At: DS RIO GRANDE
END DESCRIPTION:
XS GIS Cut Line= 4
      3054699.84     13889693.49      3054709.72     13889229.26
      3054712.95     13888989.48       3054722.3     13888442.97
#Sta/Elev= 29
  4420.7   108.4  4700.7   107.9  4740.7   105.9  4760.7   105.7  4840.7   109.1
  4860.7   109.1    4895   108.2    4915   106.7  4923.1  106.88  4933.9  107.11
  4941.9  107.28  4962.4  100.96  4985.1   93.98  4986.4   93.38    4987   92.64
    5000   91.89  5009.7   91.92  5013.2   92.56  5013.7   93.28    5014   93.92
  5032.7  101.27  5050.8  107.43  5071.2  107.37  5077.6  107.35  5214.8   106.4
  5244.8   105.2  5264.8   105.6  5284.8     107  5671.4     108
#Mann= 5 ,-1 , 0
  4420.7     .08       0  4933.9     .04       0  4941.9     .04       0
  5050.8     .04       0  5071.2     .08       0
Bank Sta=4941.9,5050.8
XS Rating Curve= 0
Exp/Cntr=.3,.1

Type RM Length L Ch R = 1 ,692.0   ,0,0,0
BEGIN DESCRIPTION:
Cross Section E135-00-00-X01
Located At: 2ND DS RIO GRANDE
END DESCRIPTION:
XS GIS Cut Line= 4
      3054961.92     13889745.91      3055154.44     13889311.48
      3055164.11     13888952.16      3055096.71     13888562.78
#Sta/Elev= 30
  4346.1     108  4596.1   107.2  4646.1   108.1  4736.1   105.1  4766.1   105.4
  4821.3   107.7  4891.3     108  4901.3   107.7  4909.7  105.34  4931.8  105.82
    4938  105.96  4960.1   99.83  4984.4   93.94  4989.7   93.16  4993.1   91.95
  5001.2   91.92  5008.9   92.45  5011.3   93.81  5029.8   100.7  5046.5  105.66
  5053.1     106  5065.4  105.17  5074.8  106.11  5091.3   106.8  5180.7   106.3
  5210.7     106  5250.7   104.5  5280.7   105.5  5450.7   105.3  5575.9     107
#Mann= 5 ,-1 , 0
  4346.1     .08       0  4931.8     .04       0    4938     .04       0
  5046.5     .04       0  5074.8     .08       0
Bank Sta=4938,5046.5
XS Rating Curve= 0
Exp/Cntr=.3,.1

Chan Stop Cuts=-1